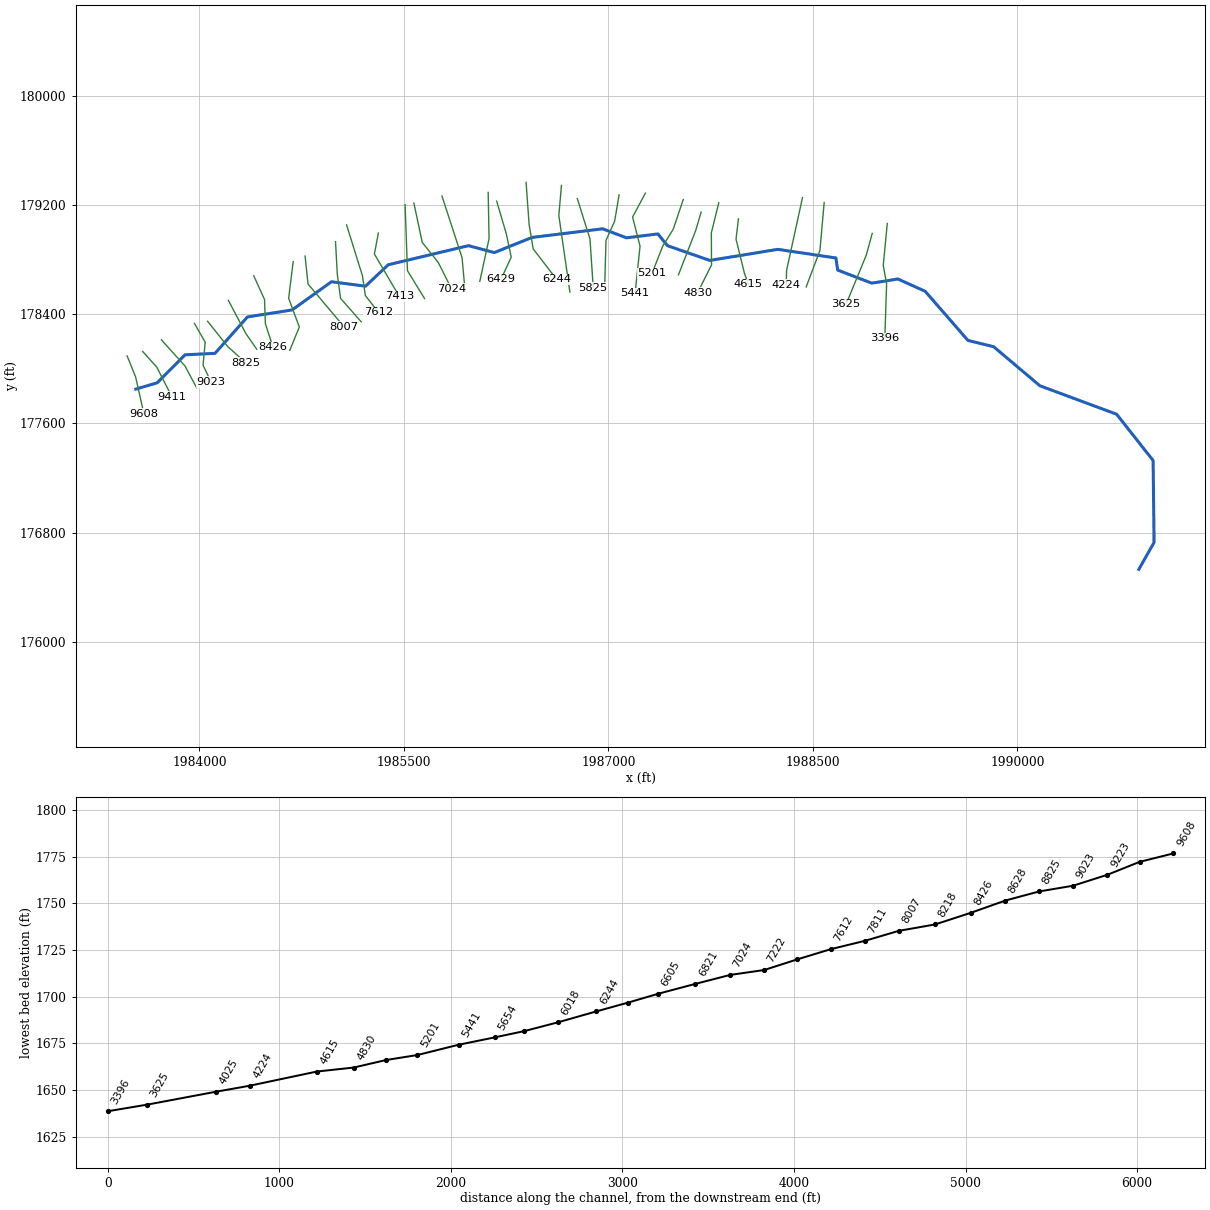
--- DRYFK.prj (project) ---

Proj Title=DRYFK
Current Plan=p01
Default Exp/Contr=0,0
English Units
Geom File=g01
Flow File=f01
Plan File=p01
BEGIN DESCRIPTION:
Stream Name: Dry Fork
Flood Zone: Approximate
Summers County, West Virginia
HEC-RAS Version: 5.0.7
Hydrology Method:
regression
Model Notes:
END DESCRIPTION:
DSS Export Rating Curves= 0
DSS Export Rating Curve Sorted= 0
DSS Export Volume Flow Curves= 0
DXF OffsetX= 0
DXF OffsetY= 0
DXF ScaleX= 0
DXF ScaleY= 0

--- DRYFK.p01 (plan) ---

Plan Title=Floodplain
Program Version=5.07
Short Identifier=Floodplain
Geom File=g01
Flow File=f01
Subcritical Flow
K Sum by GR= 0
Std Step Tol= 0.01
Critical Tol= 0.01
Num of Std Step Trials= 20
Max Error Tol= 0.3
Flow Tol Ratio= 0.001
Split Flow NTrial= 30
Split Flow Tol= 0.02
Split Flow Ratio= 0.02
Log Output Level= 0
Friction Slope Method= 1
Unsteady Friction Slope Method= 2
Unsteady Bridges Friction Slope Method= 1
Parabolic Critical Depth
Global Vel Dist= 0 , 0 , 0
Global Log Level= 0
CheckData=True
Encroach Param=-1 ,0,0, 0
Mapping Interval=1HOUR
Computation Time Step Use Courant=        0
Computation Time Step Use Time Series=    0
Computation Time Step Count To Double=0
Computation Time Step Max Doubling=0
Computation Time Step Max Halving=0
Computation Time Step Residence Courant=0
Run HTab= 0
Run UNet= 0
Run Sediment= 0
Run PostProcess= 0
Run WQNet= 0
Run RASMapper= 0
UNET Theta= 0
UNET Theta Warmup= 0
UNET ZTol= 0
UNET ZSATol= 0
UNET MxIter= 0
UNET Max Iter WO Improvement= 0
UNET MaxInSteps= 0
UNET DtIC= 0
UNET DtMin= 0
UNET MaxCRTS= 0
UNET WFStab= 0
UNET SFStab= 0
UNET WFX= 1
UNET SFX= 1
UNET 1D Methodology=Finite Difference
UNET DSS MLevel= 1
UNET Pardiso=0
UNET DZMax Abort= 0
UNET Use Existing IB Tables= 0
UNET Froude Reduction=False
UNET Froude Limit= 0
UNET Froude Power= 0
UNET D1 Cores= 0
UNET D2 Coriolis=0
UNET D2 Cores= 0
UNET D2 Theta= 1
UNET D2 Theta Warmup= 1
UNET D2 Z Tol= 0.01
UNET D2 Volume Tol= 0.01
UNET D2 Max Iterations= 20
UNET D2 Equation= 0
UNET D2 RampUpFraction=0.1
UNET D2 TimeSlices= 1
UNET D2 BCVolumeCheck=0
UNET D1D2 MaxIter= 0
UNET D1D2 ZTol=0.01
UNET D1D2 QTol=0.1
UNET D1D2 MinQTol=1
Write IC File= 0
Write IC File at Fixed DateTime=0
Write IC File at Sim End=0
Echo Input=False
Echo Parameters=False
Echo Output=False
Write Detailed= 0
HDF Write Warmup=0
HDF Write Time Slices=0
HDF Flush=0
HDF Face Node Velocities=0
HDF Compression= 1
HDF Chunk Size= 1
HDF Spatial Parts= 1
HDF Use Max Rows=0
HDF Fixed Rows= 1
Calibration Method= 0
Calibration Iterations= 20
Calibration Max Change=0.05
Calibration Tolerance=0.2
Calibration Maximum=1.5
Calibration Minimum=0.5
Calibration Optimization Method= 1
WQ AD Non Conservative
WQ ULTIMATE=-1
WQ Max Comp Step=1HOUR
WQ Output Interval=15MIN
WQ Output Selected Increments= 0
WQ Output face flow=0
WQ Output face velocity=0
WQ Output face area=0
WQ Output face dispersion=0
WQ Output cell volume=0
WQ Output cell surface area=0
WQ Output cell continuity=0
WQ Output cumulative cell continuity=0
WQ Output face conc=0
WQ Output face dconc_dx=0
WQ Output face courant=0
WQ Output face peclet=0
WQ Output face adv mass=0
WQ Output face disp mass=0
WQ Output cell mass=0
WQ Output cell source sink temp=0
WQ Output nsm pathways=0
WQ Output nsm derived pathways=0
WQ Output MaxMinRange=-1
WQ Daily Max Min Mean=-1
WQ Daily Range=0
WQ Daily Time=0
WQ Create Restart=0
WQ Fixed Restart=0
WQ System Summary=0
WQ Write To DSS=0
WQ Use Fixed Temperature=0
Sorting and Armoring Iterations= 10
XS Update Threshold= 0.02
Bed Roughness Predictor= 0
Hydraulics Update Threshold= 0.02
Energy Slope Method= 1
Volume Change Method= 1
Sediment Retention Method= 0
XS Weighting Method= 0
Number of US Weighted Cross Sections= 1
Number of DS Weighted Cross Sections= 1
Upstream XS Weight=0
Main XS Weight=1
Downstream XS Weight=0
Number of DS XS's Weighted with US Boundary= 1
Upstream Boundary Weight= 1
Weight of XSs Associated with US Boundary= 0
Number of US XS's Weighted with DS Boundary= 1
Downstream Boundary Weight= 0.5
Weight of XSs Associated with DS Boundary= 0.5
Percentile Method= 0
Sediment Output Level= 3
Mass or Volume Output= 0
Output Increment Type= 1
Profile and TS Output Increment= 1
XS Output Flag= 0
XS Output Increment= 10
Write Gradation File= 0
Read Gradation Hotstart= 0
Write HDF5 File= 1
Write Binary Output= 1
Write DSS Sediment File= 0
SV Curve= 0
Specific Gage Flag= 0

--- DRYFK.f01 (steady flow) ---

Flow Title=Flows
Program Version=5.07
Number of Profiles= 6
Profile Names=01pct,10pct,04pct,02pct,0_2pct,01plus
River Rch & RM=DRYFK,Main            ,9608
     581     307     409     492     812     860
River Rch & RM=DRYFK,Main            ,8825
     653     347     460     553     910     965
River Rch & RM=DRYFK,Main            ,7612
     726     387     512     616    1009    1073
River Rch & RM=DRYFK,Main            ,5825
     833     446     590     707    1155    1232
River Rch & RM=DRYFK,Main            ,1813
     934     503     663     794    1293    1382
Boundary for River Rch & Prof#=DRYFK,Main            , 1
Up Type= 0
Dn Type= 3
Dn Slope=0.01107
Boundary for River Rch & Prof#=DRYFK,Main            , 2
Up Type= 0
Dn Type= 3
Dn Slope=0.01107
Boundary for River Rch & Prof#=DRYFK,Main            , 3
Up Type= 0
Dn Type= 3
Dn Slope=0.01107
Boundary for River Rch & Prof#=DRYFK,Main            , 4
Up Type= 0
Dn Type= 3
Dn Slope=0.01107
Boundary for River Rch & Prof#=DRYFK,Main            , 5
Up Type= 0
Dn Type= 3
Dn Slope=0.01107
Boundary for River Rch & Prof#=DRYFK,Main            , 6
Up Type= 0
Dn Type= 3
Dn Slope=0.01107
DSS Import GetInterval= 0
DSS Import GetPeak= 0
DSS Import FillOption= 0

--- DRYFK.g01 (geometry) ---

Geom Title=Geometry
Program Version=5.07

River Reach=DRYFK           ,Main
Reach XY= 30
     1983533.488177851.8759999091983690.15003664177897.960799892
1983894.04799999178103.3099999071984114.16899999178114.233999909
     1984351.687178381.087999914     1984678.937178432.268999911
1984968.33499999 178639.233999911985218.35299999178606.782999906
     1985384.326178763.7269999091985973.51799999178903.993999907
1986162.79799999178853.3099999151986439.18699999178964.420999911
     1986957.242 179027.61599991     1987132.224178961.455999912
1987362.79799999178990.115999908     1987432.937178904.004999911
1987743.35299999178795.670999902     1988242.659178876.921999905
1988668.35299999 178813.726999911988681.54799999 178724.83799991
1988931.54799999178629.0049999071989123.21499999178659.559999912
1989323.21499999178569.2829999091989637.10299999 178208.86599991
     1989825.298178163.0329999071990164.88099999177876.226999906
     1990727.523177667.5789999061990995.17691656177328.236819336
      1991002.15176727.3149999051990890.15002109176529.388474329

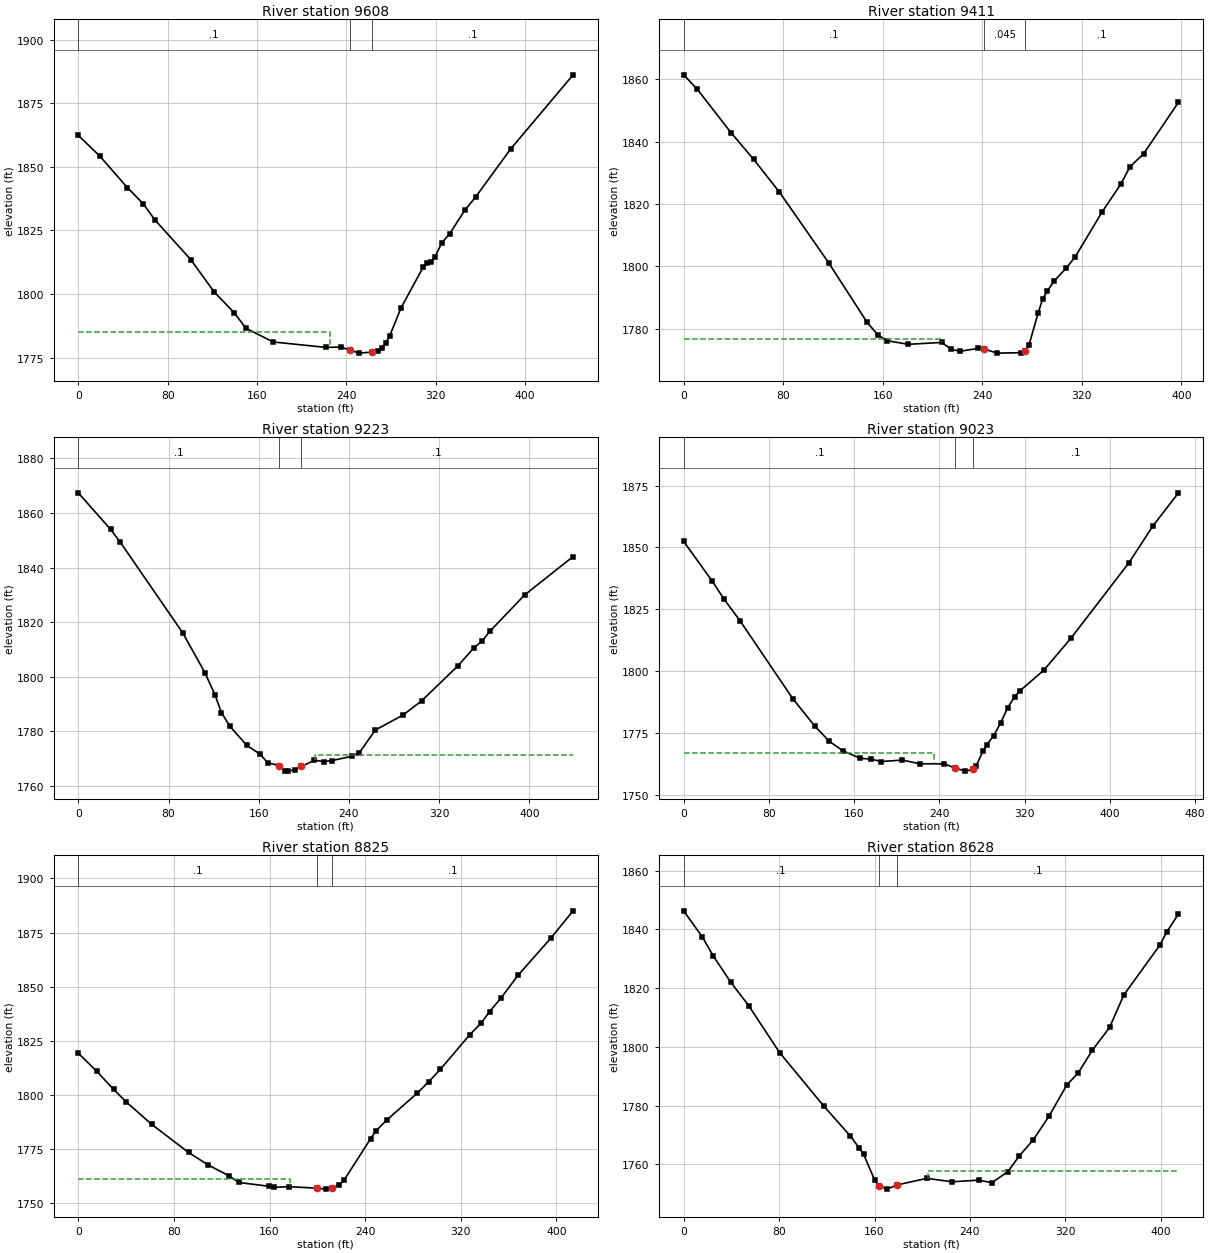
Type RM Length L Ch R = 1 ,9608    ,193.7,197.1,202.8
XS GIS Cut Line= 3
1983469.64158214178095.0858853941983531.95858676177940.984902122
1983592.51602681 177671.04858613
#Sta/Elev= 30
       0 1862.37    19.2 1854.24    43.9 1841.86    58.1 1835.52    68.7 1829.07
   100.7 1813.52   121.8 1800.73   139.5  1792.7   150.1 1786.54   174.4 1781.16
   221.5 1779.03     235 1779.15   243.21777.951   251.3 1776.77   263.11777.193
   268.6 1777.66     272 1778.78   275.3 1780.81   278.8 1783.61   288.8 1794.48
   308.9 1810.71   312.3 1812.13   315.7 1812.64     319 1814.39   325.4 1820.17
   332.5 1823.74   345.9  1832.9   355.7 1838.16   386.9 1856.96   442.9 1886.16
#Mann= 3 ,-1 , 0
       0      .1       0   243.2    .045       0   263.1      .1       0
#XS Ineff= 2 , 0
             225    1785
Permanent Ineff=
       F       F
Bank Sta=243.2,263.1
XS Rating Curve= 0 ,0
Exp/Cntr=0.3,0.1

Type RM Length L Ch R = 1 ,9411    ,185.4,187.5,199.4
XS GIS Cut Line= 3
1983583.68191641178128.0130241631983687.26334705178012.685214415
1983797.30676794177796.332333639
#Sta/Elev= 30
       0 1861.39    10.8 1856.85    38.1 1842.85    56.3 1834.29      77 1823.81
   116.7 1801.09   147.5 1782.07   156.2 1778.03   163.5 1776.22   180.6 1775.07
   207.5 1775.66     215 1773.48   222.1 1772.83   236.7 1773.75   241.6 1773.58
   251.8 1772.24   270.9 1772.38   274.31772.805   277.6 1774.87   284.9  1785.1
   288.6 1789.62   292.3 1792.11   297.7 1795.32   307.5 1799.46   314.8 1803.14
   336.5 1817.57   351.2 1826.28   358.7  1831.9   369.6 1836.07   397.7 1852.57
#Mann= 3 ,-1 , 0
       0      .1       0   241.6    .045       0   274.3      .1       0
#XS Ineff= 2 , 0
          207.09 1776.86
Permanent Ineff=
       F       F
Bank Sta=241.6,274.3
XS Rating Curve= 0 ,0
Exp/Cntr=0.3,0.1

Type RM Length L Ch R = 1 ,9223    ,211.7,200.1,187.9
XS GIS Cut Line= 3
 1983721.0947931178213.2153526881983894.15830774178021.098461491
1983979.07214718177862.290275447
#Sta/Elev= 30
       0 1867.39    28.6 1854.02    37.2 1849.31    92.6 1816.04   112.2 1801.49
   121.1 1793.42   126.9 1786.81   134.3 1781.84   149.4  1774.8     161 1771.59
     168  1768.4     1781767.353   182.9 1765.56   185.7 1765.34   191.7 1765.77
   197.81767.049   209.4  1769.3   218.2 1768.86   224.9 1769.21   242.3 1770.75
   249.3 1772.15   263.4 1780.43   287.7 1785.85   304.4  1791.1   336.4 1803.88
   350.7 1810.51     358 1813.06   365.2 1816.74   395.7 1829.93   438.7 1844.02
#Mann= 3 ,-1 , 0
       0      .1       0     178    .045       0   197.8      .1       0
#XS Ineff= 2 , 0
                          209.58         1771.31
Permanent Ineff=
       F       F
Bank Sta=178,197.8
XS Rating Curve= 0 ,0
Exp/Cntr=0.3,0.1

Type RM Length L Ch R = 1 ,9023    ,184.3,198.7,204.9
XS GIS Cut Line= 4
1983963.26634725178333.4978232021984042.21118825178195.921953142
1984026.56174942178027.4748736171984084.86322345177903.947253328
#Sta/Elev= 30
       0 1852.48    26.8 1836.35    38.1 1828.97    53.3 1820.08   102.4 1788.82
   122.9 1777.79   136.5 1771.62   149.4  1767.7   165.7 1764.68   175.6 1764.33
   185.5 1763.36   205.2 1763.94   221.7 1762.45   244.8 1762.38   254.7 1760.71
   264.5 1759.47   271.8 1760.27   274.4 1761.54     281 1767.62   284.3  1770.1
   290.9 1773.73   297.5 1779.04   304.1 1785.08   310.7 1789.66   315.8 1792.05
     338 1800.31   363.4  1813.2     418 1843.85   440.1 1858.49   464.4  1872.1
#Mann= 3 ,-1 , 0
       0      .1       0   254.7    .045       0   271.8      .1       0
#XS Ineff= 2 , 0
             235 1766.91
Permanent Ineff=
       F       F
Bank Sta=254.7,271.8
XS Rating Curve= 0 ,0
Exp/Cntr=0.3,0.1

Type RM Length L Ch R = 1 ,8825    ,199.7,196.9,193.4
XS GIS Cut Line= 3
1984059.73784948178349.4781977461984209.60391181178161.827458768
1984338.80739706178045.689203062
#Sta/Elev= 30
       0  1819.2    15.5 1810.82    29.5 1802.49    40.3  1796.6    61.3 1786.36
    92.2 1773.33   108.6 1767.56   125.8 1762.63   134.2 1759.45   159.4 1757.72
   163.6 1757.18   176.2 1757.53   199.9 1756.81   206.9 1756.38   212.61756.995
   218.1 1758.26   222.3  1760.5   244.5  1779.7   248.8 1783.17   258.1 1788.36
   283.7 1800.83     293 1805.92   302.8 1811.72   327.3 1827.67   337.1 1833.22
   344.1 1838.47   353.4 1844.56     368 1855.33   395.2 1872.34   413.9 1885.02
#Mann= 3 ,-1 , 0
       0      .1       0   199.9    .045       0   212.6      .1       0
#XS Ineff= 2 , 0
          177.31 1760.86
Permanent Ineff=
       F       F
Bank Sta=199.9,212.6
XS Rating Curve= 0 ,0
Exp/Cntr=0.3,0.1

Type RM Length L Ch R = 1 ,8628    ,207.9,202.1,195.1
XS GIS Cut Line= 3
1984212.14846491178502.8202584381984339.87782361178260.310282176
1984419.99467035 178144.58438265
#Sta/Elev= 30
       0 1846.35    15.6 1837.49    24.8 1830.98    39.6 1821.96    54.5 1814.06
    80.4 1798.06   117.5  1779.8   139.8 1769.58   147.2 1765.49   150.9 1763.34
   160.1 1754.64   163.4 1752.74   170.5 1751.51   178.9 1752.94   203.8 1755.18
   225.1 1754.01   247.3 1754.57   258.4  1753.7   271.8 1757.47   281.3 1762.79
   293.1 1768.31   306.5 1776.52   321.1 1786.94   330.8 1791.16   342.6 1798.82
     357 1806.59     369 1817.68   399.2 1834.67   404.9 1839.12   414.8 1845.25
#Mann= 3 ,-1 , 0
       0      .1       0   163.4    .045       0   178.9      .1       0
#XS Ineff= 2 , 0
                          204.79         1757.64
Permanent Ineff=
       F       F
Bank Sta=163.4,178.9
XS Rating Curve= 0 ,0
Exp/Cntr=0.3,0.1

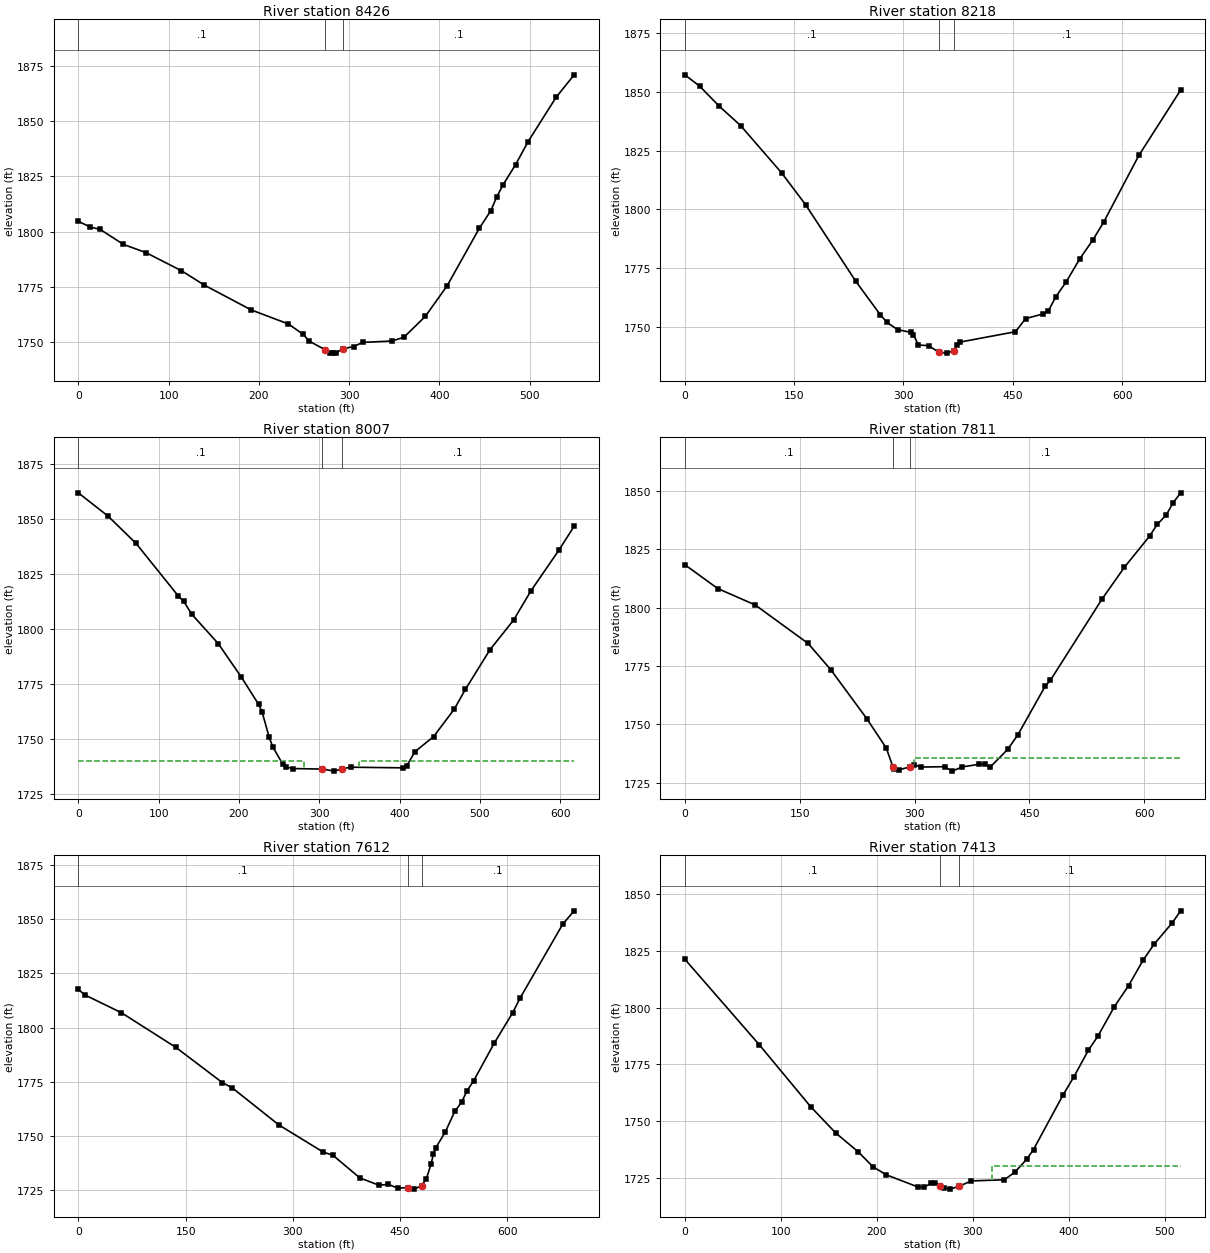
Type RM Length L Ch R = 1 ,8426    ,202.1,207.4,211.7
XS GIS Cut Line= 4
1984398.33066253178683.3859465111984477.49876614178508.981184212
1984483.50348265178332.0494921981984538.97069036178159.979291813
#Sta/Elev= 30
       0 1804.65    13.4 1802.06    24.2 1800.99      50 1794.19    74.7 1790.52
   114.3 1782.26   139.5 1775.78   191.5  1764.5   232.8 1758.12   249.2 1753.41
   255.8 1750.35   273.41746.455   278.8 1744.92     282 1744.91   285.3 1744.98
   293.1  1746.9     305 1747.85     315 1749.77   347.7 1750.41   360.8 1752.12
   384.6 1761.62   408.7 1775.48   444.5 1801.65     457 1809.43   463.8 1815.88
   470.7 1821.28   484.5 1830.37   498.3 1840.76   529.3 1860.85   549.4 1871.08
#Mann= 3 ,-1 , 0
       0      .1       0   273.4    .045       0   293.1      .1       0
Bank Sta=273.4,293.1
XS Rating Curve= 0 ,0
Exp/Cntr=0.3,0.1

Type RM Length L Ch R = 1 ,8218    ,206.2,211.7,217.4
XS GIS Cut Line= 4
1984687.59516039178786.4145149451984654.31366318178518.014201456
 1984732.5306277 178307.599550421984662.56648141178135.921201459
#Sta/Elev= 30
       0 1857.34    20.3 1852.54    46.7 1844.13    76.5 1835.73   132.7  1815.6
   165.7    1802   234.8 1769.25   268.2  1755.1   277.5 1751.79   292.1 1748.73
   310.1 1747.57   313.6 1746.57   320.6 1742.18   334.6  1741.9     349 1738.99
   359.2 1738.72   368.91739.711   373.1 1742.09     377 1743.39   453.6 1747.84
   467.6 1753.42   491.8 1755.47   498.9 1756.74     509 1762.73   523.6 1769.23
   541.7 1778.82   559.4 1786.73   574.5 1794.42   623.1 1823.05   680.3 1850.82
#Mann= 3 ,-1 , 0
       0      .1       0     349    .045       0   368.9      .1       0
Bank Sta=349,368.9
XS Rating Curve= 0 ,0
Exp/Cntr=0.3,0.1

Type RM Length L Ch R = 1 ,8007    ,205.4,195.9,186.9
XS GIS Cut Line= 3
1984774.94587679178827.9539309841984796.42617619 178622.67070328
1985061.22105784 178308.32498129
#Sta/Elev= 30
       0  1861.7    37.2 1851.05    71.9 1838.71   124.7 1814.73   131.3 1812.36
   141.2 1806.57   174.2 1793.22   203.1 1777.93   224.5 1765.59   228.8 1762.18
   237.6  1750.7   242.1 1746.29   254.5 1738.44   258.8 1737.16   267.4 1736.45
     3041736.203   318.9 1735.28   328.3 1736.37   339.4 1737.06   404.7 1736.77
     409 1737.73   419.1 1744.09   442.4 1750.98     468 1763.37     482 1772.43
   512.6 1790.45     542 1803.89   563.4 1817.08   598.4 1835.65   617.4 1846.54
#Mann= 3 ,-1 , 0
       0      .1       0     304    .045       0   328.3      .1       0
#XS Ineff= 2 , 0
          280.99 1739.69  350.08         1739.86
Permanent Ineff=
       F       F
Bank Sta=304,328.3
XS Rating Curve= 0 ,0
Exp/Cntr=0.3,0.1

Type RM Length L Ch R = 1 ,7811    ,199.1,199.1,198.2
XS GIS Cut Line= 4
1984998.13241479178933.5458244551985011.14265011178694.808006363
1985035.21158545178517.2182942681985186.67634131178345.517635565
#Sta/Elev= 30
       0 1818.43    42.9 1808.21    91.9 1801.16     161 1784.67   190.5 1773.45
   237.5 1752.49     263 1739.87   271.8 1731.72   272.9 1730.87   279.6 1730.53
   294.61731.833   299.4 1732.68   308.7 1731.71   339.1 1731.87     349 1729.97
   362.3 1731.77   384.5 1732.92   392.1 1732.91   398.7 1731.72   421.6  1739.3
   434.9 1745.57   470.4 1766.32   477.4 1768.95   544.8 1803.73   573.7 1817.22
   606.8 1830.67   616.9 1835.74   628.3 1839.61   637.4 1844.85   647.3  1849.2
#Mann= 3 ,-1 , 0
       0      .1       0   271.8    .045       0   294.6      .1       0
#XS Ineff= 2 , 0
                          299.65         1735.43
Permanent Ineff=
       F       F
Bank Sta=271.8,294.6
XS Rating Curve= 0 ,0
Exp/Cntr=0.3,0.1

Type RM Length L Ch R = 1 ,7612    ,191.7,198.4,203.2
XS GIS Cut Line= 4
     1985078.995      179056.8381985195.45091453178683.820476995
1985216.76103091178538.4565019711985312.53880354178415.980812157
#Sta/Elev= 30
       0 1817.59     8.8 1815.09    60.3 1806.81     136 1790.93   201.3 1774.63
     215 1772.23   280.3 1755.11   342.2 1742.61   355.9 1741.11   393.6 1730.67
   420.2 1727.32   433.4 1727.68   446.7 1725.94   460.21726.222   469.9  1725.5
     4801727.125   486.5 1730.22   493.1    1737   496.4 1741.63   499.7 1744.58
     513 1751.81   526.3 1761.32   536.2 1765.79     543 1770.63   552.5 1775.33
   581.6 1792.87     607 1806.68   617.6 1813.57   677.4 1847.74   693.2  1853.8
#Mann= 3 ,-1 , 0
       0      .1       0   460.2    .045       0     480      .1       0
Bank Sta=460.2,480
XS Rating Curve= 0 ,0
Exp/Cntr=0.3,0.1

Type RM Length L Ch R = 1 ,7413    ,198,190.7,183.2
XS GIS Cut Line= 3
1985312.28220488178996.6212240671985283.32068985178842.190930407
1985465.35690418178532.550899168
#Sta/Elev= 30
       0 1821.31    77.5 1783.61   130.9 1756.37   157.1 1744.72   180.5 1736.42
   195.7  1729.9   209.5 1726.31     243 1720.86     249 1720.82   256.6  1722.5
   260.4 1722.46   265.71721.452   269.4 1720.48   276.6 1719.95   285.61721.229
   298.4 1723.57   332.7 1724.07   343.7 1727.43     356 1733.12   363.1  1737.4
     394 1761.57     405 1769.33   420.2 1781.14     430 1787.26   447.2 1800.29
   462.1 1809.65   477.3 1820.91   488.7 1827.91   507.8 1837.44   516.3 1842.62
#Mann= 3 ,-1 , 0
       0      .1       0   265.7    .045       0   285.6      .1       0
#XS Ineff= 2 , 0
                             320            1730
Permanent Ineff=
       F       F
Bank Sta=265.7,285.6
XS Rating Curve= 0 ,0
Exp/Cntr=0.3,0.1

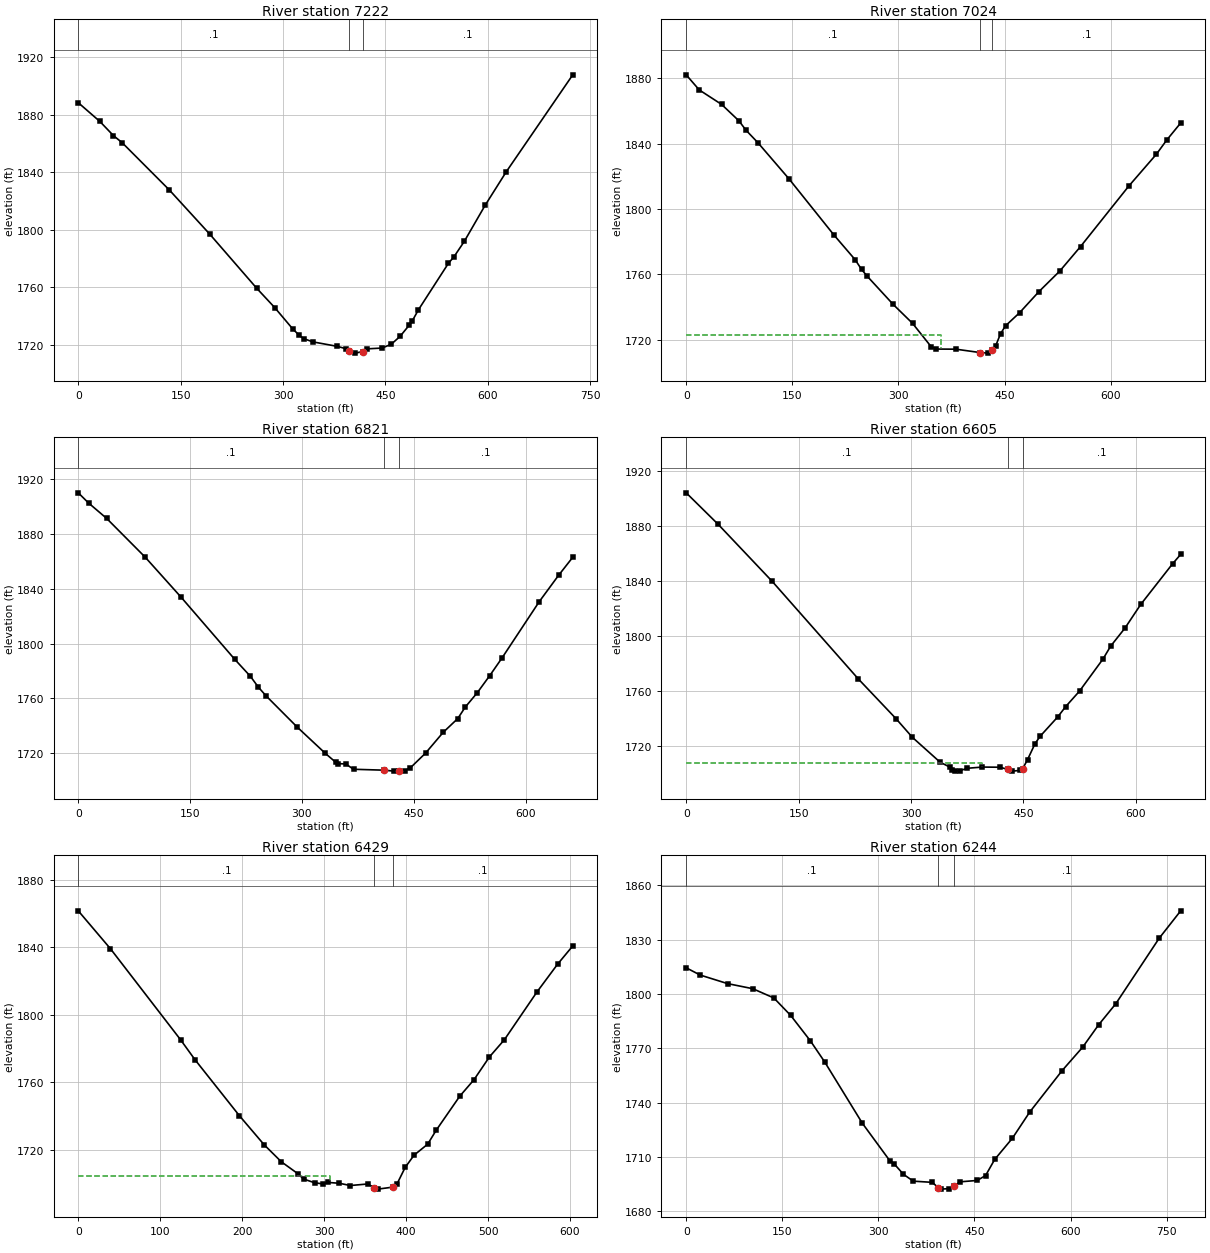
Type RM Length L Ch R = 1 ,7222    ,188.4,198.1,206.4
XS GIS Cut Line= 3
     1985508.424      179204.7821985525.76450473178720.657309225
1985651.25713877178515.852252238
#Sta/Elev= 30
       0 1888.32    31.7 1875.26    51.4 1865.52    64.5 1860.44   133.5 1827.65
   192.6 1797.02   261.5 1759.37   287.8 1745.99     314 1731.27   323.9 1726.64
   330.4 1724.38   343.6 1722.14   379.7    1719   392.8 1717.31   397.21715.608
   405.9 1714.31     4171715.426   422.4 1717.25   445.3 1717.85   458.8 1720.54
   471.5 1725.93   484.8 1733.63     489 1736.33   498.5 1744.46   542.5  1776.8
   550.2 1781.03   565.6 1791.89   596.3 1817.11   627.1 1840.27   724.6 1907.68
#Mann= 3 ,-1 , 0
       0      .1       0   397.2    .045       0     417      .1       0
Bank Sta=397.2,417
XS Rating Curve= 0 ,0
Exp/Cntr=0.3,0.1

Type RM Length L Ch R = 1 ,7024    ,207.7,202.8,197.9
XS GIS Cut Line= 4
     1985572.895       179216.381985634.23615896 178927.98526784
  1985752.023196178780.2058806741985848.44647636178588.006069258
#Sta/Elev= 30
       0 1882.04    18.4 1872.81      50 1863.94    74.4 1853.94    84.5 1848.15
   101.2 1840.57   144.9 1818.57   208.6 1784.11   238.8 1768.87   247.9 1762.89
   255.5 1758.92   292.4 1741.56   319.9 1729.92   346.2 1715.64   353.3 1714.19
   381.3  1714.1   414.81712.071   426.1 1711.69   432.7  1713.3   437.4  1716.2
   444.4 1723.64   451.3 1728.39   471.1 1736.38   498.7 1749.41   528.1 1761.97
   557.4 1776.95   625.8 1814.08   664.6 1833.47   679.2 1842.14   698.9 1852.57
#Mann= 3 ,-1 , 0
       0      .1       0   414.8    .045       0   432.7      .1       0
#XS Ineff= 2 , 0
             360    1723
Permanent Ineff=
       F       F
Bank Sta=414.8,432.7
XS Rating Curve= 0 ,0
Exp/Cntr=0.3,0.1

Type RM Length L Ch R = 1 ,6821    ,222.9,216.2,208
XS GIS Cut Line= 3
     1985778.862      179268.3141985926.39042269178815.065438538
1985943.16122105178629.222902906
#Sta/Elev= 30
       0 1910.07    13.9  1902.6      38 1891.43    89.8 1863.08   138.1 1833.77
     210 1788.45   230.9 1776.11   241.6 1768.17   251.9 1761.85   293.3 1739.24
   331.3 1719.91   345.4 1713.32   348.5 1712.38   358.9 1712.11   369.2 1708.25
   410.41707.582   423.5 1706.89   429.8 1707.04   438.2 1707.34   445.1 1709.11
   465.8 1720.01   489.4 1735.14   509.1  1745.3     519 1753.56   535.2 1764.11
     552 1776.66   568.4 1789.51   618.4 1830.67   644.2 1849.78   663.3 1863.03
#Mann= 3 ,-1 , 0
       0      .1       0   410.4    .045       0   429.8      .1       0
Bank Sta=410.4,429.8
XS Rating Curve= 0 ,0
Exp/Cntr=0.3,0.1

Type RM Length L Ch R = 1 ,6605    ,169.2,175.7,181.8
XS GIS Cut Line= 3
     1986117.824      179294.5231986124.38251542178955.744392393
1986056.39845437178642.072518036
#Sta/Elev= 30
       0  1903.8    42.7 1880.88   114.9 1839.38   229.7 1768.56   279.9 1739.75
   301.9 1726.11   338.8 1708.09   351.4 1704.66   354.8 1702.22   358.1 1701.72
   364.8 1701.82   374.9 1703.67     395 1704.56   418.6 1704.44   429.1 1702.91
   435.3 1701.61   445.4 1702.13     4491703.402   455.5 1710.02   465.5 1721.62
   472.3 1726.97   495.8 1741.03   506.4 1748.53   524.8 1759.74   556.2 1783.12
   566.4 1792.45   585.5 1805.56   606.5 1822.72   648.9  1852.2   659.8 1859.08
#Mann= 3 ,-1 , 0
       0      .1       0   429.1    .045       0     449      .1       0
#XS Ineff= 2 , 0
          394.72 1707.38
Permanent Ineff=
       F       F
Bank Sta=429.1,449
XS Rating Curve= 0 ,0
Exp/Cntr=0.3,0.1

Type RM Length L Ch R = 1 ,6429    ,188.3,185.2,185.8
XS GIS Cut Line= 4
1986180.03983978179230.4921444951986251.64691997178988.129719217
1986286.89963638 178819.577668911986211.98761402178657.635502928
#Sta/Elev= 30
       0 1861.52    39.3 1839.07   124.8 1785.26   142.3 1773.51   196.7 1740.24
   226.8 1723.11   247.7 1713.07   268.2  1705.9   274.9 1702.85   288.3 1700.64
   298.4 1699.97   305.1 1700.81   318.5 1700.34   331.9    1699     353 1699.91
   361.3 1697.69   365.4 1696.87   383.5 1698.03   388.9 1699.96   398.9 1709.76
   409.7 1716.97   426.3 1723.47   436.6 1731.64   465.5 1751.89   482.8  1761.6
   501.7 1775.13   519.9 1785.27   559.5 1813.43   584.8 1829.96   603.3 1840.76
#Mann= 3 ,-1 , 0
       0      .1       0   361.3    .045       0   383.5      .1       0
#XS Ineff= 2 , 0
          307.21 1704.37
Permanent Ineff=
       F       F
Bank Sta=361.3,383.5
XS Rating Curve= 0 ,0
Exp/Cntr(USF)=0,0
Exp/Cntr=0.3,0.1

Type RM Length L Ch R = 1 ,6244    ,227,226,225.5
XS GIS Cut Line= 4
     1986395.845      179368.7161986418.11054704179059.817673088
1986448.03408828178880.2764256951986618.99641318178658.165460461
#Sta/Elev= 30
       0 1814.41    21.8 1810.41    64.5 1805.68     104 1802.86   136.9 1797.74
   163.2 1788.07     194    1774   216.2 1762.42     275 1728.54   317.9 1707.83
   324.6 1706.14   339.1 1700.36   354.5 1696.55   384.4 1695.89   393.2    1693
   397.7 1692.15     411 1692.44   417.61693.602   427.7 1696.19   454.3 1696.94
   467.4 1699.65   481.6 1708.53   509.2 1720.24   536.2 1734.67     587 1757.67
   619.1 1770.62   643.8 1782.88   670.6 1794.51   738.4 1830.73     772 1845.88
#Mann= 3 ,-1 , 0
       0      .1       0   393.2    .045       0   417.6      .1       0
Bank Sta=393.2,417.6
XS Rating Curve= 0 ,0
Exp/Cntr=0.3,0.1

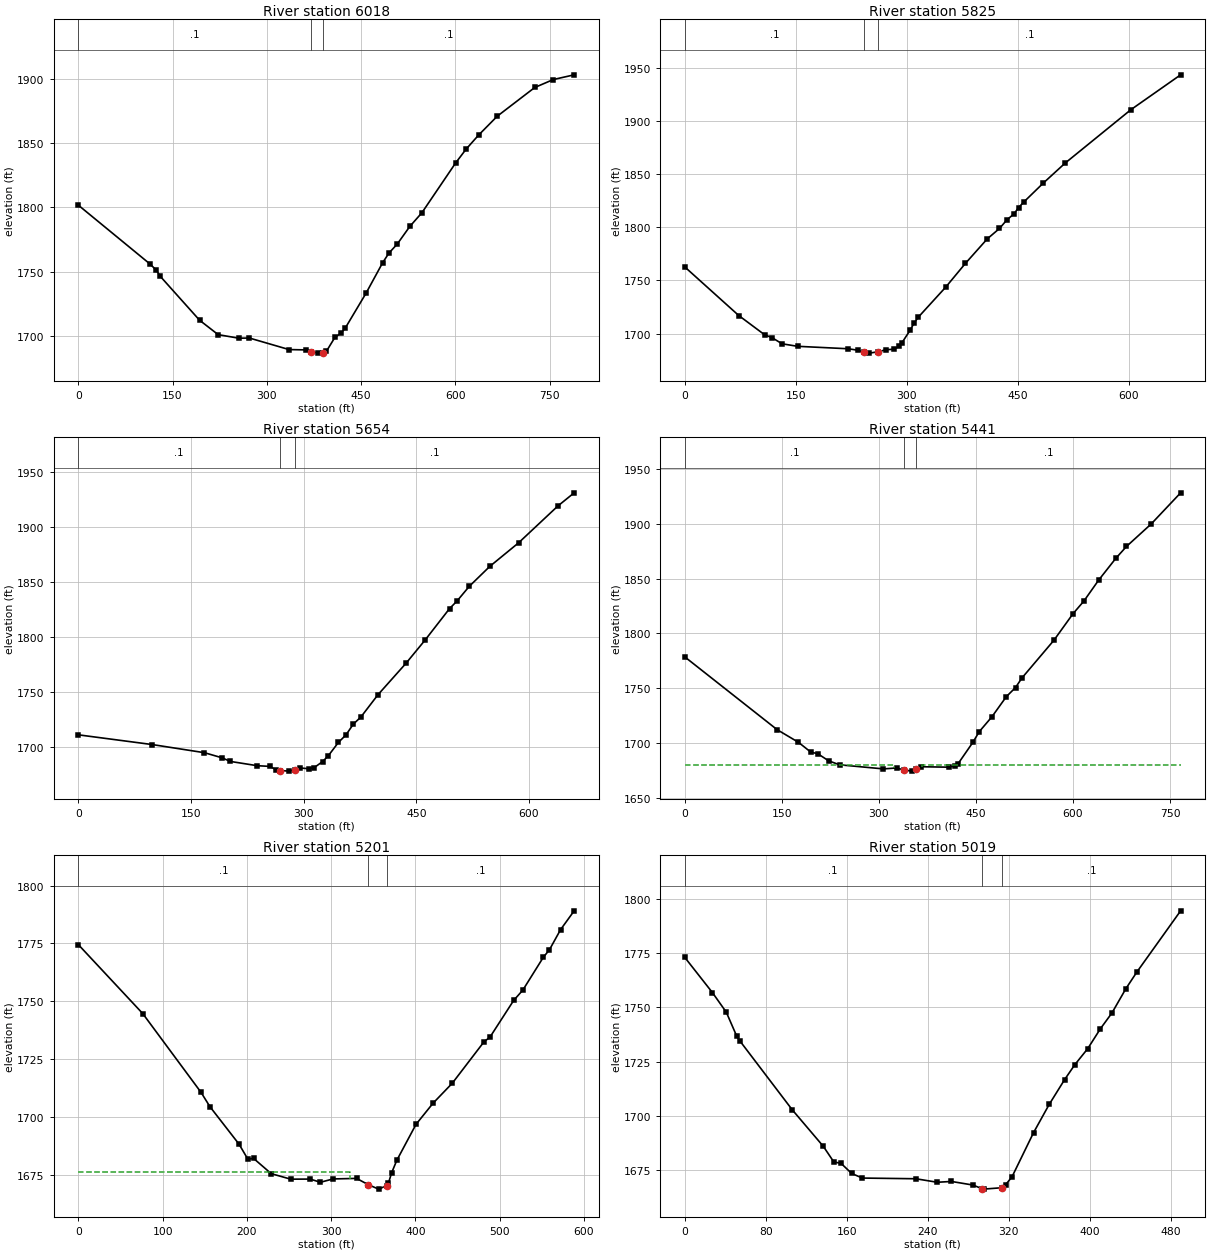
Type RM Length L Ch R = 1 ,6018    ,191.1,193.7,195.9
XS GIS Cut Line= 3
1986655.30107461179345.6918731471986636.06031823179126.032529503
     1986717.276      178563.199
#Sta/Elev= 30
       0 1801.81     114 1755.88   123.8 1751.22   130.4 1746.25     193 1711.94
   222.6 1700.67   255.4 1697.92   272.4 1698.02   335.4 1689.03   361.9 1688.77
   370.2  1687.5   381.8 1686.25   390.11686.641     395  1687.8   408.3 1698.49
   418.2 1701.96   424.9 1705.84   457.8 1732.93   484.5 1756.97   494.5 1764.46
   507.7 1771.49   527.6 1785.18   546.9 1795.92   600.5 1834.75   617.1  1845.5
     637 1856.49   666.8 1871.29   726.5 1893.73     756 1899.92   789.2 1903.61
#Mann= 3 ,-1 , 0
       0      .1       0   370.2    .045       0   390.1      .1       0
Bank Sta=370.2,390.1
XS Rating Curve= 0 ,0
Exp/Cntr=0.3,0.1

Type RM Length L Ch R = 1 ,5825    ,181.4,170.9,160
XS GIS Cut Line= 3
1986771.62448693179249.2201500851986864.57918957178953.346104472
     1986888.487      178594.188
#Sta/Elev= 30
       0 1762.72    72.9 1717.01     108  1698.8   117.6  1696.3   131.4 1690.39
   152.5 1688.01   220.8 1685.71   234.5 1684.27   242.11682.243   249.3  1681.6
   261.71682.918   272.3 1684.91   282.7  1685.2   289.5 1687.96     293 1690.87
   304.3 1702.92   310.1 1710.13   315.6 1715.47   352.6 1743.69   379.2 1766.04
   408.8 1789.16   425.3 1798.94   435.1 1806.88     445 1812.77   451.2 1818.68
   458.1 1823.82   484.4  1841.6     514 1860.46   602.8 1910.71   670.1 1943.57
#Mann= 3 ,-1 , 0
       0      .1       0   242.1    .045       0   261.7      .1       0
Bank Sta=242.1,261.7
XS Rating Curve= 0 ,0
Exp/Cntr=0.3,0.1

Type RM Length L Ch R = 1 ,5654    ,202.5,212.6,221.9
XS GIS Cut Line= 4
1987078.23345152179276.8617873611987045.58884795179083.833510143
1986982.03913797178942.9621763241986973.21118469 178633.32360073
#Sta/Elev= 30
       0 1711.21    98.6 1702.36   167.9 1694.99   191.7 1690.28   202.2 1687.09
   238.2 1683.19     255 1682.57     263 1679.63   268.41678.834   280.6 1678.27
   287.81679.605   295.5 1681.15   306.6 1680.45   313.8 1681.34   325.3    1687
   332.7 1692.13   346.2 1704.27   356.4 1711.22   366.2 1721.01   376.1 1727.31
     399 1747.67   436.2  1776.1   461.7 1797.25   494.2 1825.75   504.1  1832.6
   520.5 1845.98   547.8 1864.06   586.1 1885.43   638.6 1918.97   660.1 1930.81
#Mann= 3 ,-1 , 0
       0      .1       0   268.4    .045       0   287.8      .1       0
Bank Sta=268.4,287.8
XS Rating Curve= 0 ,0
Exp/Cntr=0.3,0.1

Type RM Length L Ch R = 1 ,5441    ,249.9,240,226.1
XS GIS Cut Line= 4
1987271.02575072179289.0342871681987177.06336839179114.087697394
1987231.71892118178899.799505156      1987195.79      178555.148
#Sta/Elev= 30
       0  1778.5   142.7 1712.11   175.6 1700.59   194.9 1691.56   205.4 1690.22
   222.3 1683.68   239.2 1680.05     307 1676.31   327.3 1677.15   339.21675.221
   351.3 1674.28   357.81675.887   364.5 1678.28   407.7 1677.89   417.7 1679.14
   422.3 1680.98   445.1 1700.45   455.1 1710.31   474.8 1723.97   496.9 1742.21
   511.1 1750.53   521.1  1759.3   570.5  1793.7   600.1 1817.99   616.9 1829.52
   639.7 1848.62   666.1  1868.4   682.6 1879.25     721  1899.9   766.3  1928.2
#Mann= 3 ,-1 , 0
       0      .1       0   339.2    .045       0   357.8      .1       0
#XS Ineff= 2 , 0
          323.31 1679.92  365.96         1680.09
Permanent Ineff=
       F       F
Bank Sta=339.2,357.8
XS Rating Curve= 0 ,0
Exp/Cntr=0.3,0.1

Type RM Length L Ch R = 1 ,5201    ,179.9,182.4,185.5
XS GIS Cut Line= 4
1987548.65723511179242.3383175771987475.70904393179025.408747909
1987398.45810463178901.2097239511987320.45834131178702.786359117
#Sta/Elev= 30
       0  1774.5    76.5 1744.65   145.7 1710.56   156.1 1704.45   190.7 1688.21
   201.1 1681.76     208 1682.04   228.9 1675.46     252 1673.09   275.1 1673.12
   287.2 1671.74   302.2 1673.18   330.1 1673.42     3441670.716   356.3 1668.78
   365.8 1670.27   367.9 1671.32   371.7 1675.82   377.9 1681.26   400.7 1696.81
   420.9 1705.94   443.7 1714.57   481.3 1732.47   488.4 1734.49   516.6 1750.41
   527.4 1754.83   551.8 1769.07   558.9 1772.23   572.2 1780.99   588.3 1789.11
#Mann= 3 ,-1 , 0
       0      .1       0     344    .045       0   365.8      .1       0
#XS Ineff= 2 , 0
          322.82 1676.18
Permanent Ineff=
       F       F
Bank Sta=344,365.8
XS Rating Curve= 0 ,0
Exp/Cntr=0.3,0.1

Type RM Length L Ch R = 1 ,5019    ,183.1,189,194.2
XS GIS Cut Line= 3
1987679.82450919179150.1454283751987640.37017314 179015.72412119
1987513.46457583178690.003676225
#Sta/Elev= 30
       0 1773.09    27.3 1756.84      41 1747.78    51.3 1736.72    54.8 1734.29
     106 1702.81   136.8 1685.87   147.2 1678.64   154.3 1678.02   164.8 1673.34
   175.4 1671.22   228.2  1670.9   249.3 1669.28   263.4 1669.65   284.5    1668
   293.21666.393   295.1 1666.11   313.21666.761   316.8 1668.07   323.3 1671.91
   344.4 1692.15   359.9 1705.23   375.1 1716.66   385.2 1723.56   397.9 1730.94
   410.5 1740.18   421.9 1747.47   435.7 1758.71   446.5 1766.36   489.7  1794.6
#Mann= 3 ,-1 , 0
       0      .1       0   293.2    .045       0   313.2      .1       0
Bank Sta=293.2,313.2
XS Rating Curve= 0 ,0
Exp/Cntr=0.3,0.1

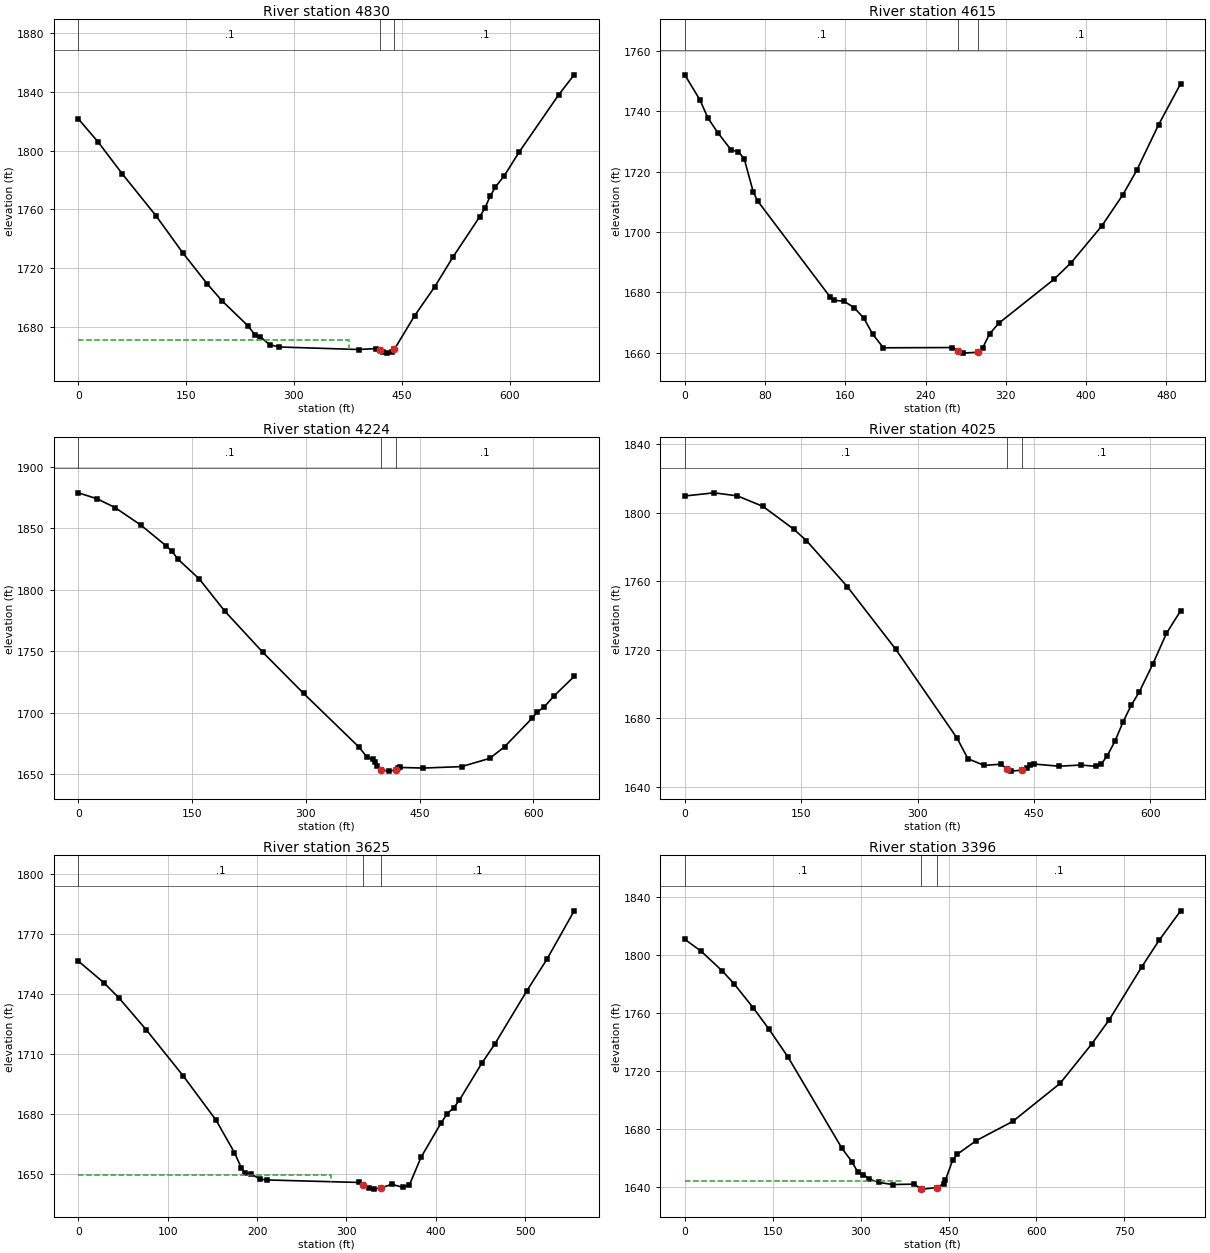
Type RM Length L Ch R = 1 ,4830    ,210.8,214.5,217.8
XS GIS Cut Line= 4
     1987809.464      179219.2021987754.74201837178998.139247342
1987756.05350351178762.4931505881987654.47544144178560.009284485
#Sta/Elev= 30
       0 1821.74    27.9 1805.75      61 1784.34   108.3 1755.54   145.5 1730.32
   179.6 1709.13   199.6  1697.9   236.5 1680.43   246.3 1674.16   252.9 1673.39
     266 1667.84   279.1 1666.26   390.2 1664.54     414 1665.18   420.2 1664.07
   423.5 1662.59   429.8 1662.07   436.6 1662.74   439.7 1664.65   467.8 1687.48
   495.8 1707.23   521.5 1727.73   558.2 1754.81   565.6 1760.79   572.9 1768.86
   580.3 1775.31   592.5 1782.85   613.3 1799.06   668.3 1838.11   689.9 1851.75
#Mann= 3 ,-1 , 0
       0      .1       0   420.2    .045       0   439.7      .1       0
#XS Ineff= 2 , 0
          377.01 1671.04
Permanent Ineff=
       F       F
Bank Sta=420.2,439.7
XS Rating Curve= 0 ,0
Exp/Cntr=0.3,0.1

Type RM Length L Ch R = 1 ,4615    ,396.6,391.3,382.9
XS GIS Cut Line= 4
1987953.58615392179100.7160853581987935.88539673178952.316581565
1987997.59422266178701.0096271611988026.88032475178620.213547184
#Sta/Elev= 30
       0    1752    15.1 1743.69    22.9 1737.82    32.8  1732.9      46 1727.22
    53.5 1726.52    59.2 1724.27    68.2 1713.27    72.5 1710.32   145.2 1678.36
   148.5 1677.45   158.6  1677.1   168.7 1675.01   178.5 1671.49   187.4 1666.14
     198  1661.7   266.7 1661.79   272.5 1660.72   276.8 1659.94   292.51660.244
   297.1  1661.8   303.8 1666.31   312.8 1669.78     368 1684.36   385.2  1689.9
   415.6 1701.99   436.5 1712.27   450.5 1720.43   472.2 1735.47   494.2 1749.06
#Mann= 3 ,-1 , 0
       0      .1       0   272.5    .045       0   292.5      .1       0
Bank Sta=272.5,292.5
XS Rating Curve= 0 ,0
Exp/Cntr=0.3,0.1

Type RM Length L Ch R = 1 ,4224    ,201.2,199.3,196.9
XS GIS Cut Line= 3
     1988423.474      179256.6031988306.81042697178723.645225648
1988303.42051177178615.467617967
#Sta/Elev= 30
       0 1879.05      25 1874.13    48.5 1867.01    82.1 1852.92   115.7 1835.93
   123.6 1831.28   131.8 1824.75   159.4 1808.96   192.9  1782.8   243.3 1749.14
     297 1715.67     370 1671.97     381 1663.46   388.1 1661.82   391.1 1659.95
   394.4  1656.2   398.71653.408   410.1 1652.34   418.61653.379   421.3 1654.98
   424.7 1655.32   454.9 1654.84   505.3 1656.02   542.4 1662.72     562 1672.17
   598.1 1695.27   604.7 1700.23   614.5 1704.78   627.6 1713.81   653.8 1729.48
#Mann= 3 ,-1 , 0
       0      .1       0   398.7    .045       0   418.6      .1       0
Bank Sta=398.7,418.6
XS Rating Curve= 0 ,0
Exp/Cntr=0.3,0.1

Type RM Length L Ch R = 1 ,4025    ,396.3,399.3,394.3
XS GIS Cut Line= 3
     1988582.411      179220.8351988551.27719936178869.415992179
1988450.68496885178601.539823397
#Sta/Elev= 30
       0 1809.63    37.5 1811.48    67.7 1809.71   100.6 1803.58   140.1 1790.37
   156.6 1783.66   209.3  1756.8   271.9 1720.13   350.9 1668.29   364.8 1656.31
   385.8 1652.41   406.9 1653.13   415.21650.468   420.9 1649.08   434.9 1649.73
   441.4 1650.75   445.4 1652.93   449.5 1653.24   482.2 1651.94   510.3 1652.63
   529.5  1651.9   536.5 1653.12     544 1657.78   554.1 1666.37   564.6 1677.66
   575.1 1687.43   585.6 1695.27   603.1  1711.6   620.6 1729.43   638.9 1742.65
#Mann= 3 ,-1 , 0
       0      .1       0   415.2    .045       0   434.9      .1       0
Bank Sta=415.2,434.9
XS Rating Curve= 0 ,0
Exp/Cntr=0.3,0.1

Type RM Length L Ch R = 1 ,3625    ,219.6,228.8,238.7
XS GIS Cut Line= 3
1988934.87152372178993.9320095491988892.06471363178836.950262458
1988743.37426807178474.311532955
#Sta/Elev= 30
       0 1756.53    28.5 1745.71    45.5 1738.04    76.1 1722.03   117.4 1698.94
   154.1 1676.77   174.7 1660.47   182.3 1652.95   185.9 1650.47     193 1649.77
   203.6 1647.22   210.7  1646.8   313.5 1645.55   318.51644.449   325.6 1642.67
   331.3  1642.2   338.5 1642.84   350.7  1644.6   363.2 1643.09   370.3 1644.21
   383.4 1658.17   405.7  1675.3   412.8 1680.09   419.9 1682.98   426.2 1686.74
   451.3 1705.26     466    1715   501.6 1741.51   524.3 1757.51   554.7 1781.74
#Mann= 3 ,-1 , 0
       0      .1       0   318.5    .045       0   338.5      .1       0
#XS Ineff= 2 , 0
          282.25 1649.05
Permanent Ineff=
       F       F
Bank Sta=318.5,338.5
XS Rating Curve= 0 ,0
Exp/Cntr=0.3,0.1

Type RM Length L Ch R = 1 ,3396    ,380.7,370.3,353.4
XS GIS Cut Line= 4
     1989045.226       179066.371989015.59997951178759.540149551
1989040.37770088 178625.34235895     1989027.044      178224.217
#Sta/Elev= 30
       0 1810.72    27.9 1802.53    64.2 1788.84    83.9  1780.2   116.9 1763.48
   143.3 1749.04   176.2 1729.61   268.3  1666.7     285 1657.65   294.9 1650.62
   304.8 1648.75   314.7 1645.55   331.4 1643.27   354.8 1641.83   391.5 1642.12
   402.81638.811   404.8 1638.68   430.3 1639.72   441.5 1642.43   444.8 1645.01
   456.9  1658.4   464.5 1662.59   497.7 1672.16   559.7 1685.34   640.3 1711.45
   694.3  1738.6   723.9 1755.06   779.5 1791.57   809.2 1809.95   846.1 1830.35
#Mann= 3 ,-1 , 0
       0      .1       0   402.8    .045       0   430.3      .1       0
#XS Ineff= 2 , 0
       0   368.1    1644               0
Permanent Ineff=
       F       F
Bank Sta=402.8,430.3
XS Rating Curve= 0 ,0
Exp/Cntr=0.3,0.1