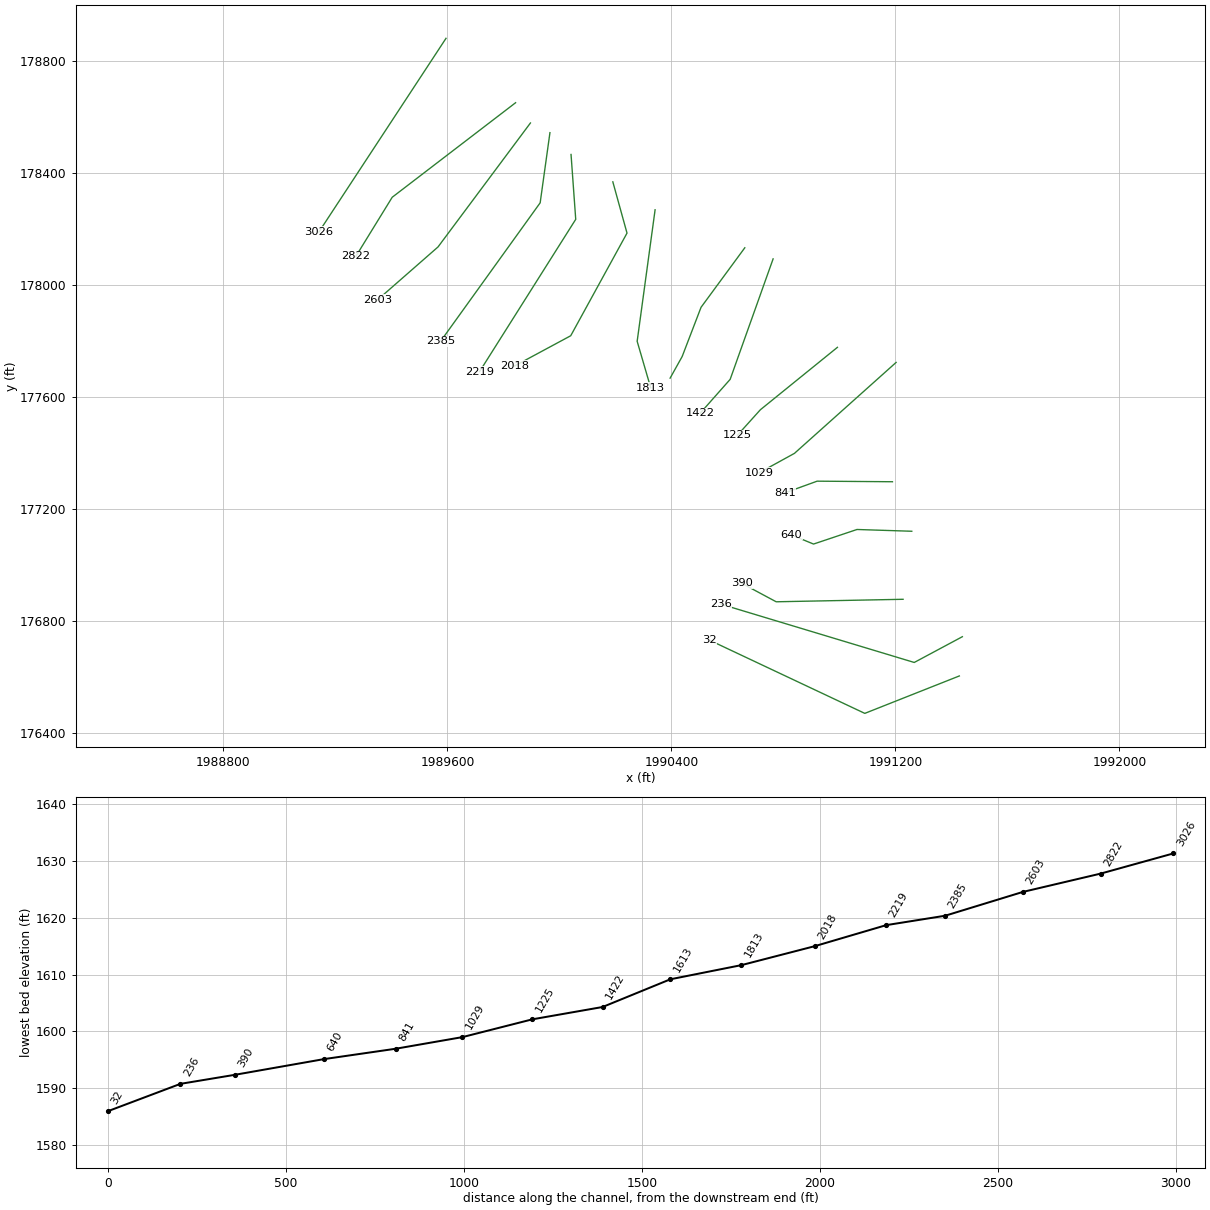
HEC-RAS study DRYFK.prj: DRYFK

--- DRYFK.g01 (geometry) --- (continued)

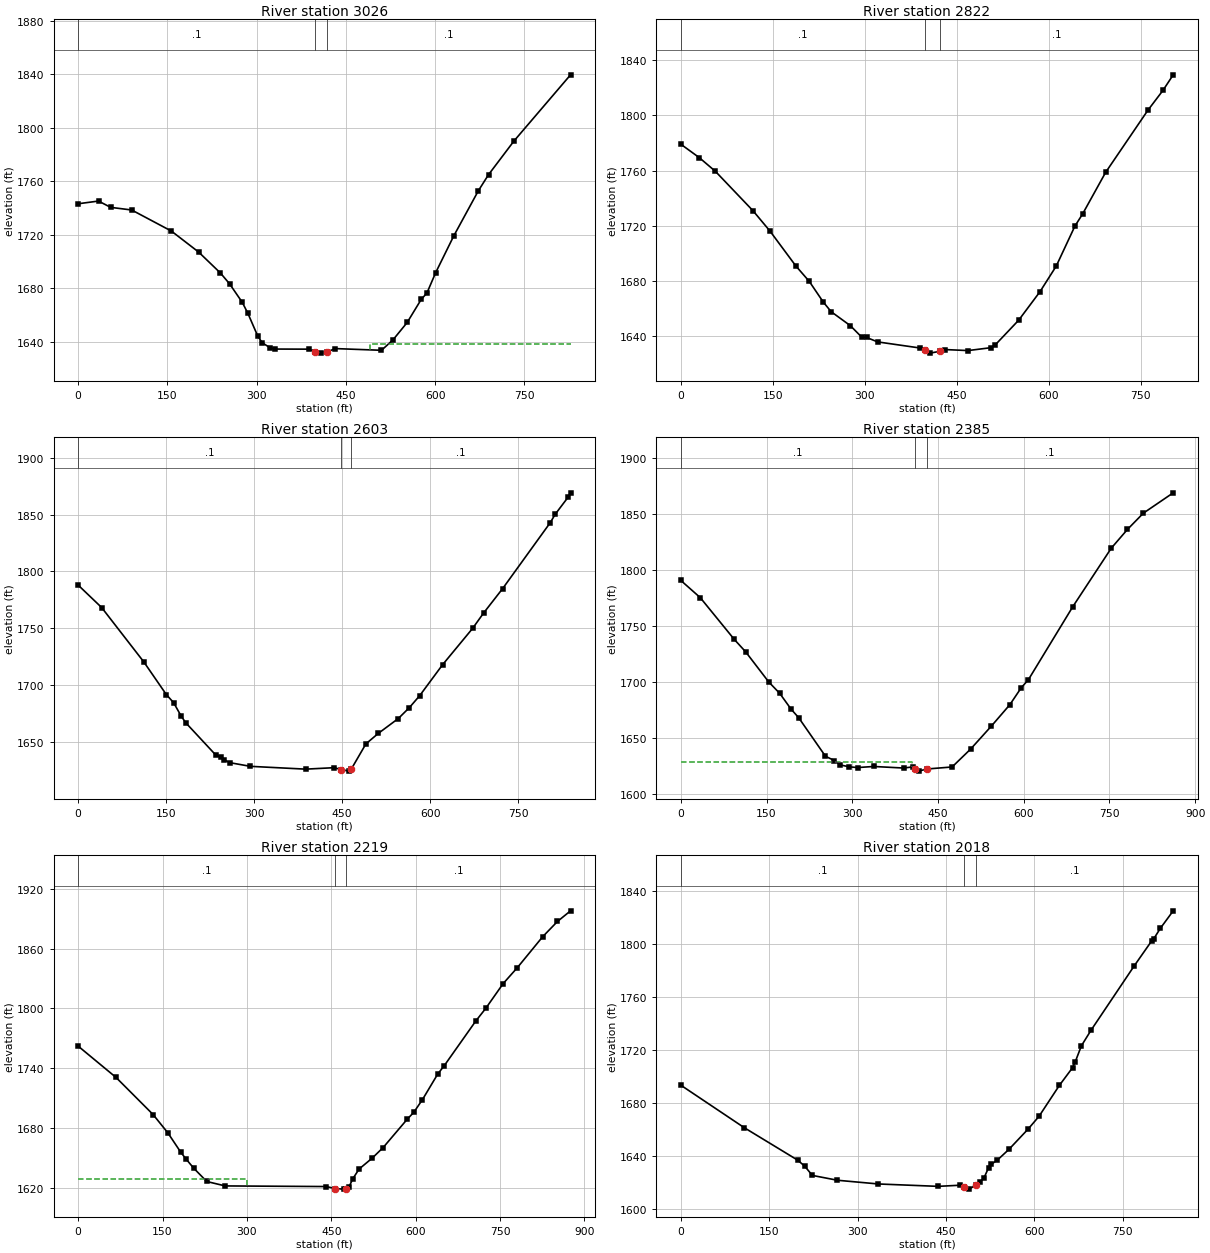
Type RM Length L Ch R = 1 ,3026    ,209.3,204.3,198.4
XS GIS Cut Line= 2
     1989595.139      178880.873     1989140.915      178188.941
#Sta/Elev= 30
       0 1743.19    34.2 1745.21    54.6  1740.5      90 1738.52   156.7 1722.75
   202.5 1707.04   239.1 1691.37   254.6 1683.21   275.9 1669.36   285.4 1661.07
   301.5 1644.53   309.1 1639.24   323.3 1635.19   330.4 1634.42   388.2 1634.34
   397.61632.505   407.9 1631.37   417.6 1632.18   432.3 1634.77   509.9 1633.49
   529.3 1641.33   553.1 1654.32   576.6 1671.53   586.3  1676.4     601 1691.62
   631.3 1719.04   672.7  1752.9   689.9 1765.01   732.5 1790.11   827.7 1839.71
#Mann= 3 ,-1 , 0
       0      .1       0   397.6    .045       0   417.6      .1       0
#XS Ineff= 2 , 0
                             490         1638.32
Permanent Ineff=
       F       F
Bank Sta=397.6,417.6
XS Rating Curve= 0 ,0
Exp/Cntr=0.3,0.1

Type RM Length L Ch R = 1 ,2822    ,216.8,218.5,222.5
XS GIS Cut Line= 3
     1989843.681      178650.915 1989402.9683161178313.261405278
 1989273.1984384178102.372315504
#Sta/Elev= 30
       0 1779.13    30.1  1769.4    56.4 1759.46   117.8 1730.87   145.4 1716.18
   187.5 1690.96   209.5 1679.73   231.9 1665.01     245 1657.86   276.4 1647.69
   295.1 1639.31   302.9 1639.13   320.9 1635.94   389.7 1631.54   397.4 1629.85
   406.2 1627.81   422.7 1629.15   430.9 1630.39   468.3 1629.66   506.2 1631.79
   512.8 1633.85   550.9  1651.7   585.7 1672.39   612.1 1690.88   642.5  1719.8
     655 1728.56   692.6 1758.73   761.5 1803.73     786 1818.07   802.8 1829.39
#Mann= 3 ,-1 , 0
       0      .1       0   397.4    .045       0   422.7      .1       0
Bank Sta=397.4,422.7
XS Rating Curve= 0 ,0
Exp/Cntr=0.3,0.1

Type RM Length L Ch R = 1 ,2603    ,220.5,218.4,219.7
XS GIS Cut Line= 3
     1989896.628      178578.5171989566.56295316178135.786011132
1989350.62786437177946.814753901
#Sta/Elev= 30
       0 1788.04      40 1768.35   112.1  1720.4   150.4 1691.76   162.7 1684.73
     175 1673.45   183.2 1667.18   234.9 1638.51   244.3 1636.92   248.9 1634.47
   258.3 1632.03   293.5 1628.79   387.8 1626.32     436  1627.6   448.2    1626
   461.5 1624.58   465.6 1626.45   490.4  1648.5   511.5 1657.72   545.7 1670.82
   564.5 1680.38     582 1690.83   621.2 1718.14   672.3 1750.01   690.9 1763.42
   723.4 1784.91   804.8 1843.03     813 1850.22   834.8 1865.12   839.2 1869.11
#Mann= 3 ,-1 , 0
       0      .1       0   448.2    .045       0   465.6      .1       0
Bank Sta=448.2,465.6
XS Rating Curve= 0 ,0
Exp/Cntr=0.3,0.1

Type RM Length L Ch R = 1 ,2385    ,164.1,165.6,165.6
XS GIS Cut Line= 3
     1989966.346      178543.9891989931.42856794178293.431752301
     1989576.084      177799.352
#Sta/Elev= 30
       0 1790.53    33.9 1775.24    93.5 1737.93   113.4 1726.86   153.8 1699.96
     173  1689.8   192.9  1675.7   206.2 1668.06   253.1 1633.64   268.6 1629.83
   278.6 1625.93   295.1  1624.2   309.2 1623.56   337.3 1624.53   389.9 1623.14
   405.5 1624.14   410.61622.698   416.1 1620.38   430.51622.274   474.7 1624.09
   507.1 1640.06   543.4 1660.57   575.8 1679.71   595.9 1694.96   608.1  1701.9
   685.8 1767.06   753.2 1819.33   781.6 1836.11   809.4 1850.59   861.6 1868.72
#Mann= 3 ,-1 , 0
       0      .1       0   410.6    .045       0   430.5      .1       0
#XS Ineff= 2 , 0
          404.33 1628.22
Permanent Ineff=
       F       F
Bank Sta=410.6,430.5
XS Rating Curve= 0 ,0
Exp/Cntr=0.3,0.1

Type RM Length L Ch R = 1 ,2219    ,200.2,201.4,202.1
XS GIS Cut Line= 3
1990041.69995081178466.0634274641990058.44251204178234.421894912
      1989715.06      177690.717
#Sta/Elev= 30
       0 1762.14    67.4  1730.7   133.2 1693.52   159.5 1675.12   182.5 1655.65
   191.9 1648.82   205.5 1639.68   228.6 1626.38   261.4 1621.93   441.3  1621.3
   457.31619.178   472.4 1618.72   476.81618.808   481.1 1620.45   488.2 1629.11
   499.5  1638.9   522.8 1649.86   542.2 1660.44   584.9 1688.78   596.6 1695.73
   612.1 1708.54   639.2 1734.14   650.9 1742.61     707 1787.44   724.6 1800.02
   755.6 1824.92   780.8 1840.89   825.9 1871.95   852.1 1887.18   875.3 1897.83
#Mann= 3 ,-1 , 0
       0      .1       0   457.3    .045       0   476.8      .1       0
#XS Ineff= 2 , 0
             300 1628.64
Permanent Ineff=
       F       F
Bank Sta=457.3,476.8
XS Rating Curve= 0 ,0
Exp/Cntr=0.3,0.1

Type RM Length L Ch R = 1 ,2018    ,199.4,205.2,210.1
XS GIS Cut Line= 4
1990190.96221027 178368.28735251 1990241.5786022178185.234713204
1990040.58465378177818.6527001481989839.96795541177710.674526899
#Sta/Elev= 30
       0 1693.43   107.9  1661.3   198.3 1636.88   210.4 1632.28   223.2 1625.35
   265.9 1621.69   335.4 1618.89   436.5 1617.09   473.8 1617.94   480.21616.764
   488.8    1615   500.2 1617.74   507.6 1620.15   514.8 1623.68   522.5 1631.26
   526.9 1633.73   537.5 1636.99   557.1 1645.08   589.8 1660.47     608 1669.94
   642.6 1693.32     665 1706.69   669.7 1711.29   679.9 1723.12   696.3 1734.91
   769.3 1783.28   799.1 1802.23   802.9 1804.01     814 1811.84   835.8 1825.02
#Mann= 3 ,-1 , 0
       0      .1       0   480.2    .045       0   500.2      .1       0
Bank Sta=480.2,500.2
XS Rating Curve= 0 ,0
Exp/Cntr=0.3,0.1

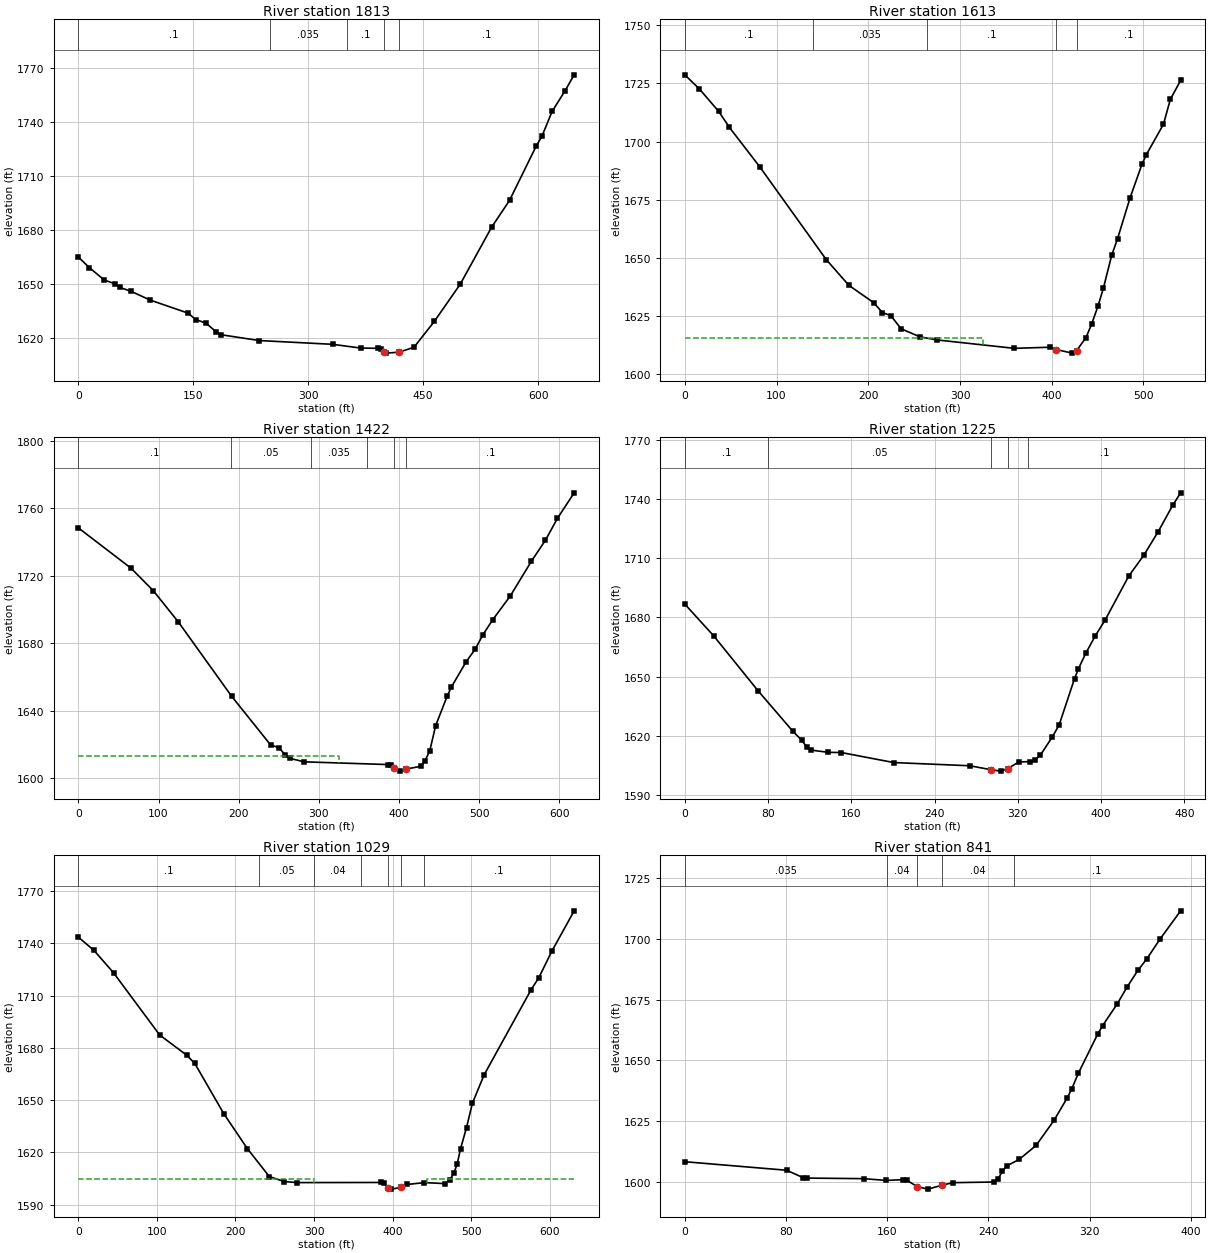
Type RM Length L Ch R = 1 ,1813    ,199.8,199.8,194.7
XS GIS Cut Line= 3
     1990341.927      178268.5131990277.84329478177798.764451518
1990326.28058202177632.803697694
#Sta/Elev= 30
       0 1665.12    14.2 1659.26      34 1652.28    47.3 1650.29    53.9 1648.21
    68.3 1646.13    93.6 1641.19   143.3 1633.89   153.2  1630.3   166.5 1628.39
   179.7 1623.52   186.3 1621.89     236 1618.67     332 1616.56   368.5 1614.48
   391.6 1614.34   394.9 1613.99     3991612.371   401.6 1611.67   418.4  1612.2
     438 1614.92   464.5 1629.28   498.4 1650.03   539.4 1681.75   562.7 1696.59
   597.5 1726.82     605 1732.29   618.2 1746.02   635.1 1757.52     647 1766.39
#Mann= 5 ,-1 , 0
       0      .1       0     250    .035       0     350      .1       0
     399    .045       0   418.4      .1       0
Bank Sta=399,418.4
XS Rating Curve= 0 ,0
Exp/Cntr=0.3,0.1

Type RM Length L Ch R = 1 ,1613    ,189.4,190.5,190.8
XS GIS Cut Line= 4
     1990662.296      178132.8291990506.06173732177920.311285833
1990438.56645006177744.3681022761990395.54182726177667.245713445
#Sta/Elev= 30
       0 1728.64    15.8 1722.62    36.9 1712.97    48.7 1706.03    81.5 1689.26
   154.2 1649.32   178.8 1638.29   205.9 1630.83   215.5 1626.55   224.6 1625.27
   235.8 1619.63   256.2 1616.18   274.8 1614.84   359.1 1611.23   397.8  1611.7
   404.8 1610.72   422.4 1609.17   427.1 1610.27   437.3  1615.8   443.5 1621.64
   450.5 1629.45   456.3 1637.05   465.4 1651.24   471.8 1658.37   485.4 1675.84
   498.3  1690.2   503.1 1694.35   521.8 1707.41   529.3 1718.13   540.5 1726.22
#Mann= 5 ,-1 , 0
       0      .1       0     140    .035       0  263.77      .1       0
   404.8    .045       0   427.1      .1       0
#XS Ineff= 2 , 0
             325 1615.83
Permanent Ineff=
       F       F
Bank Sta=404.8,427.1
XS Rating Curve= 0 ,0
Exp/Cntr=0.3,0.1

Type RM Length L Ch R = 1 ,1422    ,205.5,197,191.8
XS GIS Cut Line= 3
     1990763.391      178093.1751990609.99084553177662.891536581
1990502.94698338177541.931208492
#Sta/Elev= 30
       0 1748.51    65.6 1724.64    93.5 1711.24   124.8 1692.67   191.1  1648.7
   239.9 1619.74   250.2 1618.19   257.9 1613.94   264.1 1611.82   281.5 1609.79
   386.3 1608.17   389.5 1607.89   393.8 1606.01   401.7 1604.28   409.21605.532
   427.4 1607.17   432.5 1610.55   438.3 1616.43   445.6 1631.27   459.8 1648.56
     465 1653.98   483.6 1669.11   495.2 1676.81   504.5 1685.14   516.7 1693.99
   538.7 1708.16   564.9 1728.66   582.5 1741.19   597.5  1754.2   618.3 1769.28
#Mann= 6 ,-1 , 0
       0      .1       0     190     .05       0     290    .035       0
     360      .1       0   393.8    .045       0   409.2      .1       0
#XS Ineff= 2 , 0
             325 1613.12
Permanent Ineff=
       F       F
Bank Sta=393.8,409.2
XS Rating Curve= 0 ,0
Exp/Cntr=0.3,0.1

Type RM Length L Ch R = 1 ,1225    ,196.4,196.7,197.7
XS GIS Cut Line= 3
1990993.07025156177777.2273351751990717.95912674177554.374810612
1990636.11396367177463.527918867
#Sta/Elev= 30
       0 1686.68    27.9 1670.51    70.3 1642.84   103.9 1622.23   112.4 1617.72
   117.4 1614.08   120.8 1612.79   137.7 1611.63   150.4 1611.52   200.8 1606.44
   273.8 1604.83   294.3 1602.81   303.6 1602.11   310.41603.427   320.7  1606.7
   331.6 1606.96   336.4 1607.71   341.6 1610.23   353.1 1619.46   359.6  1625.5
   374.4 1648.95   378.1  1653.9   385.1 1661.71   394.4 1670.68   403.7 1678.54
   426.4 1700.82   440.9  1711.4   454.8 1723.39   468.7 1736.71   476.3 1743.02
#Mann= 5 ,-1 , 0
       0      .1       0      80     .05       0   294.3    .045       0
   310.4     .05       0     330      .1       0
Bank Sta=294.3,310.4
XS Rating Curve= 0 ,0
Exp/Cntr=0.3,0.1

Type RM Length L Ch R = 1 ,1029    ,198.6,187.5,177.3
XS GIS Cut Line= 3
     1991202.701      177723.3681990839.59949876177398.538276556
1990713.50334598  177329.2325757
#Sta/Elev= 30
       0 1743.57    19.9 1735.99    44.9 1723.07   103.5 1687.45   138.3 1675.71
   148.2 1671.11     185 1642.37   215.2 1622.17   243.1 1606.18     262 1603.34
     278 1602.72   385.2 1602.79   389.5 1602.35   394.2 1599.75   398.4 1598.97
   410.91599.945   418.8 1601.65   440.6 1602.72   466.2 1602.15     473 1604.33
   477.9 1608.08   482.1 1613.21   486.5 1622.15   494.1  1634.3   501.5 1648.18
   516.5 1664.56   576.4 1713.49   586.1 1720.29     603 1735.77   631.1 1758.68
#Mann= 7 ,-1 , 0
       0      .1       0     230     .05       0     300     .04       0
     360     .05       0   394.2    .045       0   410.9     .05       0
     440      .1       0
#XS Ineff= 2 , 0
             300 1604.77  444.14         1604.77
Permanent Ineff=
       F       F
Bank Sta=394.2,410.9
XS Rating Curve= 0 ,0
Exp/Cntr=0.3,0.1

Type RM Length L Ch R = 1 ,841     ,196.4,201.5,205.3
XS GIS Cut Line= 3
1991189.64108659177297.2125413261990920.61107795177299.230062875
1990805.15362414177257.361581271
#Sta/Elev= 30
       0 1608.21    80.5 1604.69    93.6 1601.63    96.9 1601.47   141.3 1601.23
   159.2 1600.51   172.4 1600.81   175.6 1600.53   183.71597.965     192 1596.92
   203.41598.531   211.7 1599.58   244.5 1599.85   247.8 1601.28   251.1 1604.32
   254.4 1606.47   264.2 1609.13   277.7 1614.93   291.8 1625.23   302.3 1634.51
   305.7 1638.03     311 1644.58   326.3 1660.71   330.2 1664.26   341.7 1673.13
   349.5 1680.09   358.1 1687.01   365.1  1691.7   375.6 1699.89   391.9 1711.55
#Mann= 5 ,-1 , 0
       0    .035       0     160     .04       0   183.7    .045       0
   203.4     .04       0     260      .1       0
Bank Sta=183.7,203.4
XS Rating Curve= 0 ,0
Exp/Cntr=0.3,0.1

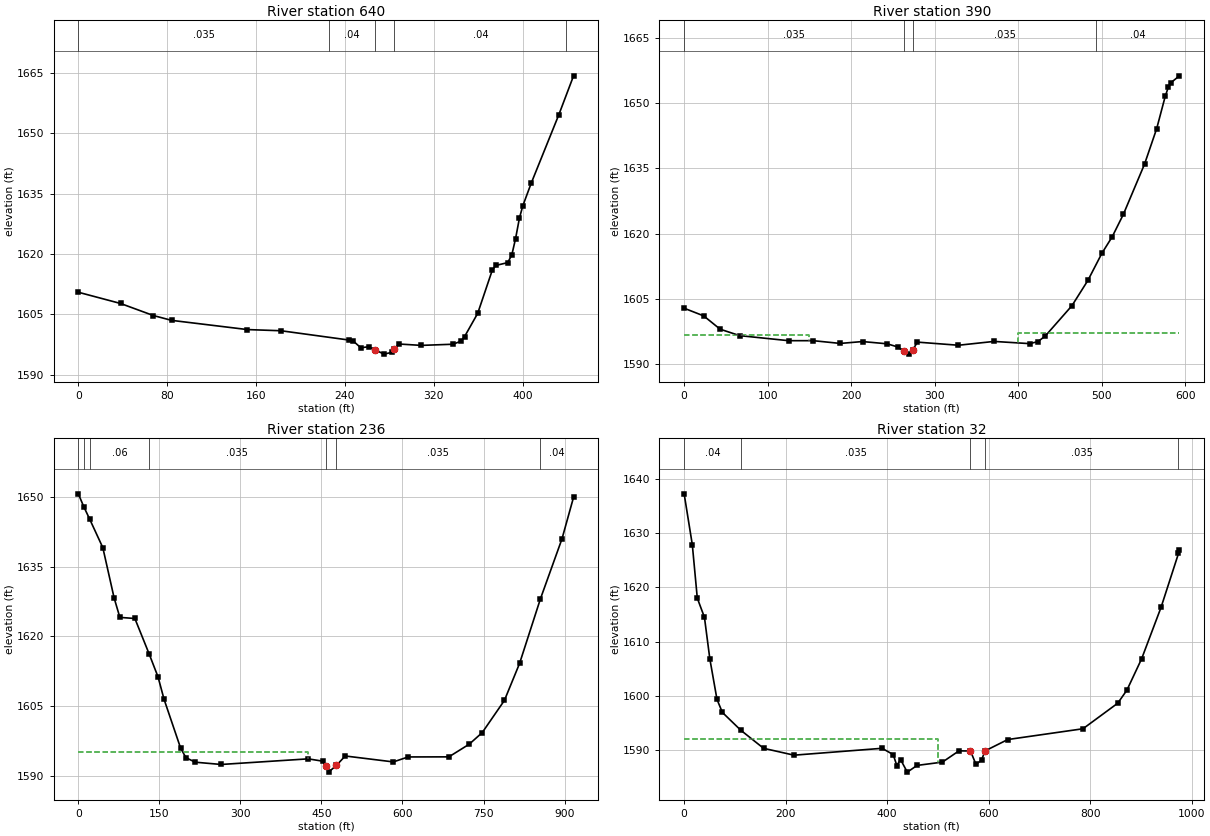
Type RM Length L Ch R = 1 ,640     ,254.4,249.5,244.9
XS GIS Cut Line= 4
1991258.70070168177120.3809505891991063.03563919177126.686340019
 1990907.8480371177074.647380811 1990827.8741206177107.550265932
#Sta/Elev= 30
       0 1610.47      38 1607.68    67.6 1604.68      84 1603.48   152.3 1601.19
   182.5  1600.9     244 1598.58   247.5 1598.35   254.4 1596.66   261.3 1596.93
   267.21596.159   275.2 1595.09   282.1 1595.52   284.61596.462     289  1597.6
   308.7 1597.26   337.4 1597.55   344.4 1598.29   347.8 1599.46   359.6 1605.23
   372.7 1615.94   375.9 1617.13   386.6 1617.83   390.3 1619.74   393.7 1623.82
   397.2 1628.95   400.3 1632.02   407.8 1637.59   432.7 1654.63   445.9 1664.25
#Mann= 5 ,-1 , 0
       0    .035       0  225.77     .04       0   267.2    .045       0
   284.6     .04       0  439.45     .05       0
Bank Sta=267.2,284.6
XS Rating Curve= 0 ,0
Exp/Cntr=0.3,0.1

Type RM Length L Ch R = 1 ,390     ,162.6,153.5,149.7
XS GIS Cut Line= 3
1991227.66412676176877.388487225 1990774.3582597176868.465143385
1990651.21611472176934.497887799
#Sta/Elev= 30
       0 1602.88    23.4 1601.12    43.1 1598.06    66.5 1596.58   125.1 1595.42
   154.6 1595.42     187 1594.79   213.6 1595.22   243.2  1594.7   256.4 1593.94
   262.9 1592.97   269.5 1592.33     274 1593.37   279.3 1595.09   328.5 1594.37
   371.1 1595.25   413.9 1594.74   423.7 1595.21   432.5  1596.5   464.4 1603.46
   483.5 1609.27   500.4 1615.55   512.6 1619.29     526 1624.46   551.3 1635.97
   565.9 1644.16   576.1 1651.56   579.8 1653.66   582.8 1654.69   593.1 1656.29
#Mann= 4 ,-1 , 0
       0    .035       0   262.9    .045       0     274    .035       0
  493.39     .04       0
#XS Ineff= 2 , 0
             150 1596.77     400         1597.12
Permanent Ineff=
       F       F
Bank Sta=262.9,274
XS Rating Curve= 0 ,0
Exp/Cntr(USF)=0,0
Exp/Cntr=0.3,0.1

Type RM Length L Ch R = 1 ,236     ,204.1,204.1,204.1
XS GIS Cut Line= 3
1991439.37976208176743.7775263641991267.50476211176651.763637483
 1990576.5325399176860.096970811
#Sta/Elev= 30
       0 1650.69    10.2  1647.9      21 1645.25    45.4 1639.09    66.3 1628.26
    76.9 1624.07   104.7 1623.83   131.3 1616.14   147.6 1611.24   158.7 1606.43
   189.5 1595.86   199.3 1593.84   216.4 1592.87   264.4 1592.38   425.5 1593.59
   452.9 1593.08   457.7 1592.07   463.2 1590.73   477.91592.187     494 1594.21
   583.1 1592.93   610.5    1594   685.9 1594.02   723.6 1596.75   747.6 1599.24
   788.7 1606.18   816.8 1614.16   855.2 1628.01   895.3    1641   916.7 1649.96
#Mann= 7 ,-1 , 0
       0    .035       0    10.2      .1       0      21     .06       0
   131.3    .035       0   457.7    .045       0   477.9    .035       0
   855.2     .04       0
#XS Ineff= 2 , 0
             425    1595
Permanent Ineff=
       F       F
Bank Sta=457.7,477.9
XS Rating Curve= 0 ,0
Exp/Cntr(USF)=0,0
Exp/Cntr=0.3,0.1

Type RM Length L Ch R = 1 ,32      ,,,
XS GIS Cut Line= 3
1991428.52906767 176603.586554171991090.85545653176469.905998588
1990536.60198432176731.190720826
#Sta/Elev= 30
       0  1637.3    16.1  1627.9    25.9 1618.04      40 1614.49    50.6 1606.83
    64.7 1599.34    75.3 1596.93   111.6 1593.64   156.5  1590.3   216.5 1589.03
   390.1  1590.3   411.9 1589.14   419.1 1587.12   426.4 1588.23   439.7  1585.9
     459 1587.14   508.9 1587.75   541.6 1589.83   564.2  1589.8   575.1 1587.32
     586 1588.13   592.9 1589.82   637.7 1591.92   785.9 1593.91   854.4 1598.63
   872.5 1601.05   901.5 1606.84   939.8 1616.35   974.1 1626.29   975.9 1626.89
#Mann= 5 ,-1 , 0
       0     .04       0   111.6    .035       0   564.2    .045       0
   592.9    .035       0   974.1     .04       0
#XS Ineff= 2 , 0
             500    1592
Permanent Ineff=
       F       F
Bank Sta=564.2,592.9
XS Rating Curve= 0 ,0
Exp/Cntr(USF)=0,0
Exp/Cntr=0.3,0.1
LCMann Table=0

Chan Stop Cuts=-1
Use User Specified Reach Order=0
Composite Channel Slope=5